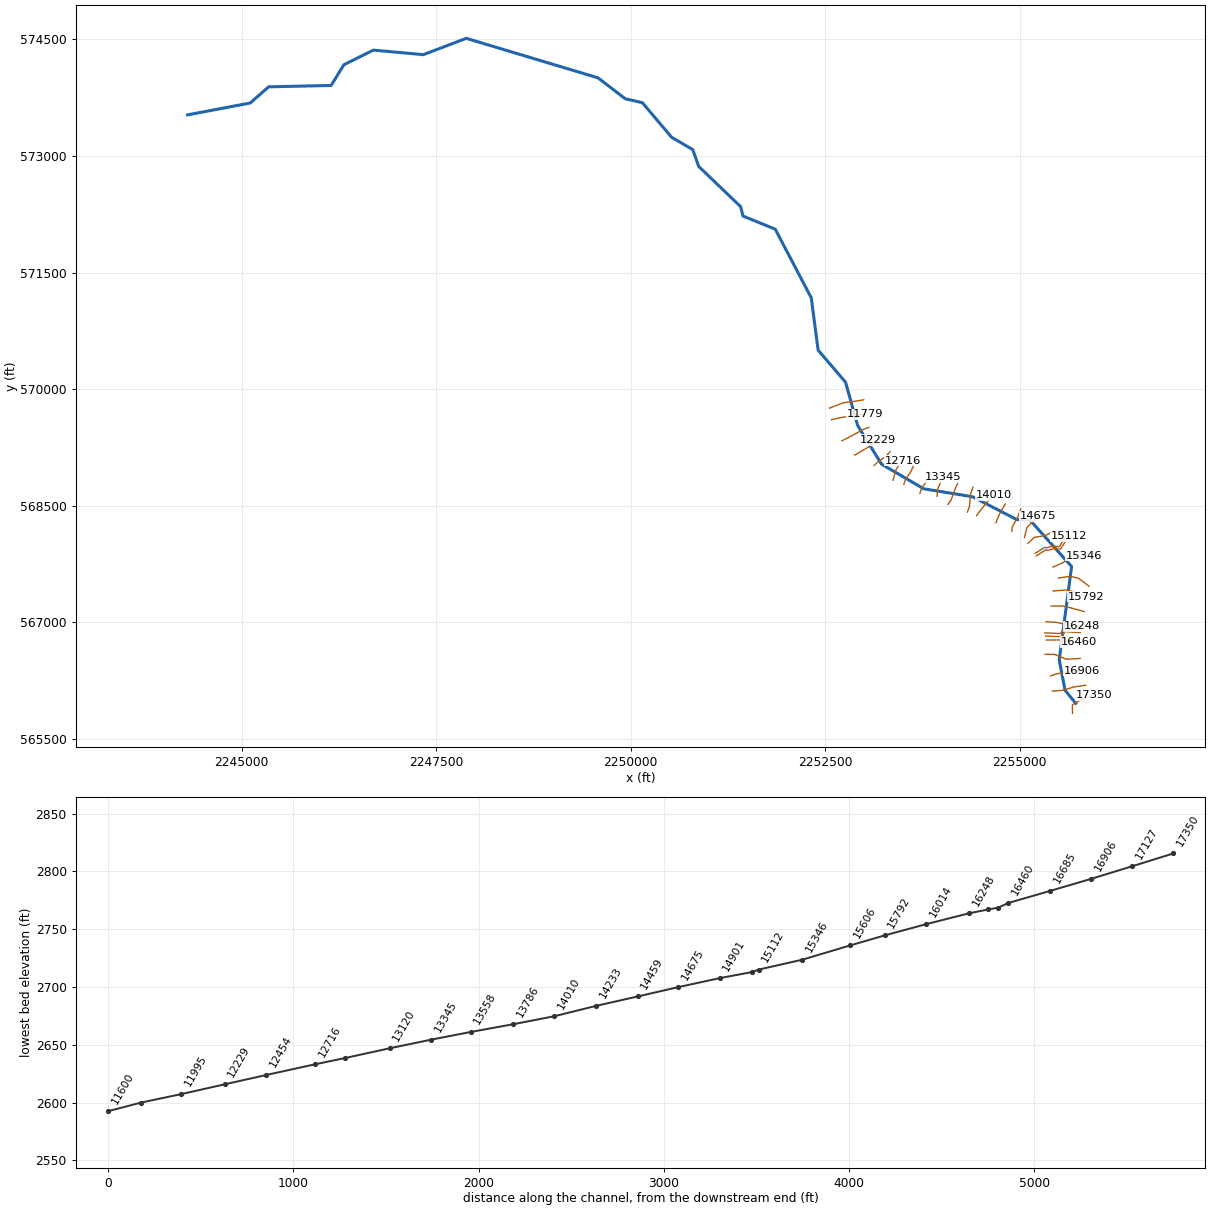
--- CONLEYRN.prj (project) ---

Proj Title=CONLEYRN
Current Plan=p01
Default Exp/Contr=0,0
English Units
Geom File=g01
Flow File=f01
Plan File=p01
BEGIN DESCRIPTION:
----------MODEL BY WOOD PLC 2022----------
AFH study
Randolph County, WV
HEC-RAS Version: RAS 6.2
Vertical Datum: NAVD88
Projection: NAD 1983 StatePlane West Virginia S FIPS 4702 (US Feet)
Terrain: 1-meter LIDAR (FEMA Region III 3DEP collected 2016-2018)
Land Use: 2019 NLCD
Hydrologic Method:
WV SIR2010-5033 regression equations
Additional Model Notes:
None
END DESCRIPTION:
DSS File=dss
DSS Export Rating Curves= 0
DSS Export Rating Curve Sorted= 0
DSS Export Volume Flow Curves= 0
DXF OffsetX= 0
DXF OffsetY= 0
DXF ScaleX= 0
DXF ScaleY= 0

--- CONLEYRN.p01 (plan) ---

Plan Title=Floodplain
Program Version=6.20
Short Identifier=Floodplain
Geom File=g01
Flow File=f01
Subcritical Flow
K Sum by GR= 0
Std Step Tol= 0.01
Critical Tol= 0.01
Num of Std Step Trials= 20
Max Error Tol= 0.3
Flow Tol Ratio= 0.001
Split Flow NTrial= 30
Split Flow Tol= 0.02
Split Flow Ratio= 0.02
Log Output Level= 0
Friction Slope Method= 1
Unsteady Friction Slope Method= 2
Unsteady Bridges Friction Slope Method= 1
Parabolic Critical Depth
Global Vel Dist= 0 , 0 , 0
Global Log Level= 0
CheckData=True
Encroach Param=-1 ,0,0, 0
Computation Interval=0.1SEC
Output Interval=1SEC
Instantaneous Interval=Max Profile
Mapping Interval=1HOUR
Computation Time Step Use Courant=        0
Computation Time Step Use Time Series=    0
Computation Time Step Count To Double=0
Computation Time Step Max Doubling=0
Computation Time Step Max Halving=0
Computation Time Step Residence Courant=0
Run HTab= 0
Run UNet= 0
Run Sediment= 0
Run PostProcess= 0
Run WQNet= 0
Run RASMapper=-1
UNET Theta= 0
UNET Theta Warmup= 0
UNET ZTol= 0
UNET ZSATol= 0
UNET MxIter= 0
UNET Max Iter WO Improvement= 0
UNET MaxInSteps= 0
UNET DtIC= 0
UNET DtMin= 0
UNET MaxCRTS= 0
UNET WFStab= 0
UNET SFStab= 0
UNET WFX= 1
UNET SFX= 1
UNET Gravity=32.174
UNET 1D Methodology=Finite Difference
UNET DSS MLevel= 1
UNET Pardiso=0
UNET DZMax Abort= 0
UNET Use Existing IB Tables= 0
UNET Froude Reduction=False
UNET Froude Limit= 0
UNET Froude Power= 0
UNET D1 Cores= 0
UNET WindReference=Eulerian
UNET WindDragFormulation=Hsu (1988)
UNET D2 Coriolis=0
UNET D2 Cores= 0
UNET D2 Theta= 1
UNET D2 Theta Warmup= 1
UNET D2 Z Tol= 0.01
UNET D2 Volume Tol= 0.01
UNET D2 Max Iterations= 20
UNET D2 Equation= 0
UNET D2 RampUpFraction=0.1
UNET D2 TimeSlices= 1
UNET D2 Turbulence Formulation=Non-Conservative (original)
UNET D2 Eddy Viscosity=0.3
UNET D2 Transverse Eddy Viscosity=0.1
UNET D2 Smagorinsky Mixing=0
UNET D2 BCVolumeCheck=0
UNET D2 Cores=0
UNET D2 SolverType=PARDISO (Direct)
UNET D2 Minimum Iterations= 2147483647
UNET D2 Maximum Iterations= 2147483647
UNET D2 Restart Number= 10
UNET D2 Relaxation Coeff=1.3
UNET D2 SOR Precondition Iterations= 10
UNET D2 ILUT Maximum Fill= 8
UNET D2 ILUT Tolerance=1E-08
UNET D1D2 MaxIter= 0
UNET D1D2 ZTol=0.01
UNET D1D2 QTol=0.1
UNET D1D2 MinQTol=1
DSS File=dss
Write IC File= 0
Write IC File at Fixed DateTime=0
Write IC File at Sim End=0
Echo Input=False
Echo Parameters=False
Echo Output=False
Write Detailed= 0
HDF Write Warmup=0
HDF Write Time Slices=0
HDF Flush=0
HDF Compression= 1
HDF Chunk Size= 1
HDF Spatial Parts= 1
HDF Use Max Rows=0
HDF Fixed Rows= 1
Calibration Method= 0
Calibration Iterations= 20
Calibration Max Change=0.05
Calibration Tolerance=0.2
Calibration Maximum=1.5
Calibration Minimum=0.5
Calibration Optimization Method= 1
WQ AD Non Conservative
WQ ULTIMATE=-1
WQ Max Comp Step=1HOUR
WQ Output Interval=15MIN
WQ Output Selected Increments= 0
WQ Output face flow=0
WQ Output face velocity=0
WQ Output face area=0
WQ Output face dispersion=0
WQ Output cell volume=0
WQ Output cell surface area=0
WQ Output cell continuity=0
WQ Output cumulative cell continuity=0
WQ Output face conc=0
WQ Output face dconc_dx=0
WQ Output face courant=0
WQ Output face peclet=0
WQ Output face adv mass=0
WQ Output face disp mass=0
WQ Output cell mass=0
WQ Output cell source sink temp=0
WQ Output nsm pathways=0
WQ Output nsm derived pathways=0
WQ Create Restart=0
WQ Fixed Restart=0
WQ System Summary=0
WQ Write To DSS=0
Sorting and Armoring Iterations= 10
XS Update Threshold= 0.02
Bed Roughness Predictor= 0
Hydraulics Update Threshold= 0.02
Energy Slope Method= 1
Volume Change Method= 1
Sediment Retention Method= 0
Sediment TS Multiplier= 1
Warm Up Method= 0
XS Weighting Method= 0
Number of US Weighted Cross Sections= 1
Number of DS Weighted Cross Sections= 1
Upstream XS Weight=0
Main XS Weight=1
Downstream XS Weight=0
Number of DS XS's Weighted with US Boundary= 1
Upstream Boundary Weight= 1
Weight of XSs Associated with US Boundary= 0
Number of US XS's Weighted with DS Boundary= 1
Downstream Boundary Weight= 0.5
Weight of XSs Associated with DS Boundary= 0.5
Percentile Method= 0
Sediment Output Level= 3
Mass or Volume Output= 0
Output Increment Type= 1
Profile and TS Output Increment= 1
Transport Output Increment 1
XS Output Flag= 0
XS Output Increment= 10
Read HDF5 Sediment Hotstart= 0
Sediment Hotstart Type= 0
Write Gradation File= 0
Read Gradation Hotstart= 0
Write HDF5 File= 1
Write Binary Output= 1
Write DSS Sediment File= 0
DSS Sediment Output Type= 1
SV Curve= 0
Specific Gage Flag= 0
Subcell Erosion Methods= 0
Subcell Deposition Methods= 0
Advection Scheme= 1
Matrix Solver= 0
Implicit Weighting Factor= 1
Maximum Outer Loop Convergence Iterations= 5
Convergence Maximum Absolute= 0.001
Convergence RMSE= 0.0001
Grain Fractions Max Abs Error= 0.001
Max Subgrid Regions= 1
Max Subgrid Length Scale= 3.402823E+38
Initial Layer Thickness= 3.402823E+38
Min Layer Thickness= 3.402823E+38
Max Layer Thickness= 3.402823E+38
Number of Layers= 5

--- CONLEYRN.f01 (steady flow) ---

Flow Title=Flow
Program Version=6.20
Number of Profiles= 1
Profile Names=P100yr
River Rch & RM=CONLEYRN,Main,17350
     540
River Rch & RM=CONLEYRN,Main,14459
     600
River Rch & RM=CONLEYRN,Main,11600
     673
River Rch & RM=CONLEYRN,Main,8009
     848
River Rch & RM=CONLEYRN,Main,5777
     967
Boundary for River Rch & Prof#=CONLEYRN,Main            , 1
Up Type= 0
Dn Type= 3
Dn Slope=0.02211
DSS Import GetInterval= 0
DSS Import GetPeak= 0
DSS Import FillOption= 0

--- CONLEYRN.g01 (geometry) ---

Geom Title=Geometry
Program Version=6.20

River Reach=CONLEYRN        ,Main
Reach XY= 30
     2255719.305      565960.245     2255582.847      566128.474
     2255507.881      566518.574     2255666.701      567719.099
     2255135.604      568312.704     2254960.569      568323.352
     2254396.774      568615.289      2253765.89      568719.383
     2253224.798      569035.091     2252917.289      569532.723
     2252762.368      570089.038     2252409.684      570501.488
      2252321.62       571174.07     2251858.558      572057.412
     2251443.754      572226.295  2251414.245486572346.713276153
     2250874.975      572864.431     2250798.529      573080.494
     2250527.261      573238.932     2250150.756        573684.3
     2249930.569      573734.6312249581.18436858574003.195400586
      2247888.16      574511.311     2247336.329      574301.481
     2246694.393      574359.8532246316.31466344574172.175631425
      2246151.35      573905.306     2245348.874      573887.772
     2245111.975      573679.766     2244306.209      573526.641

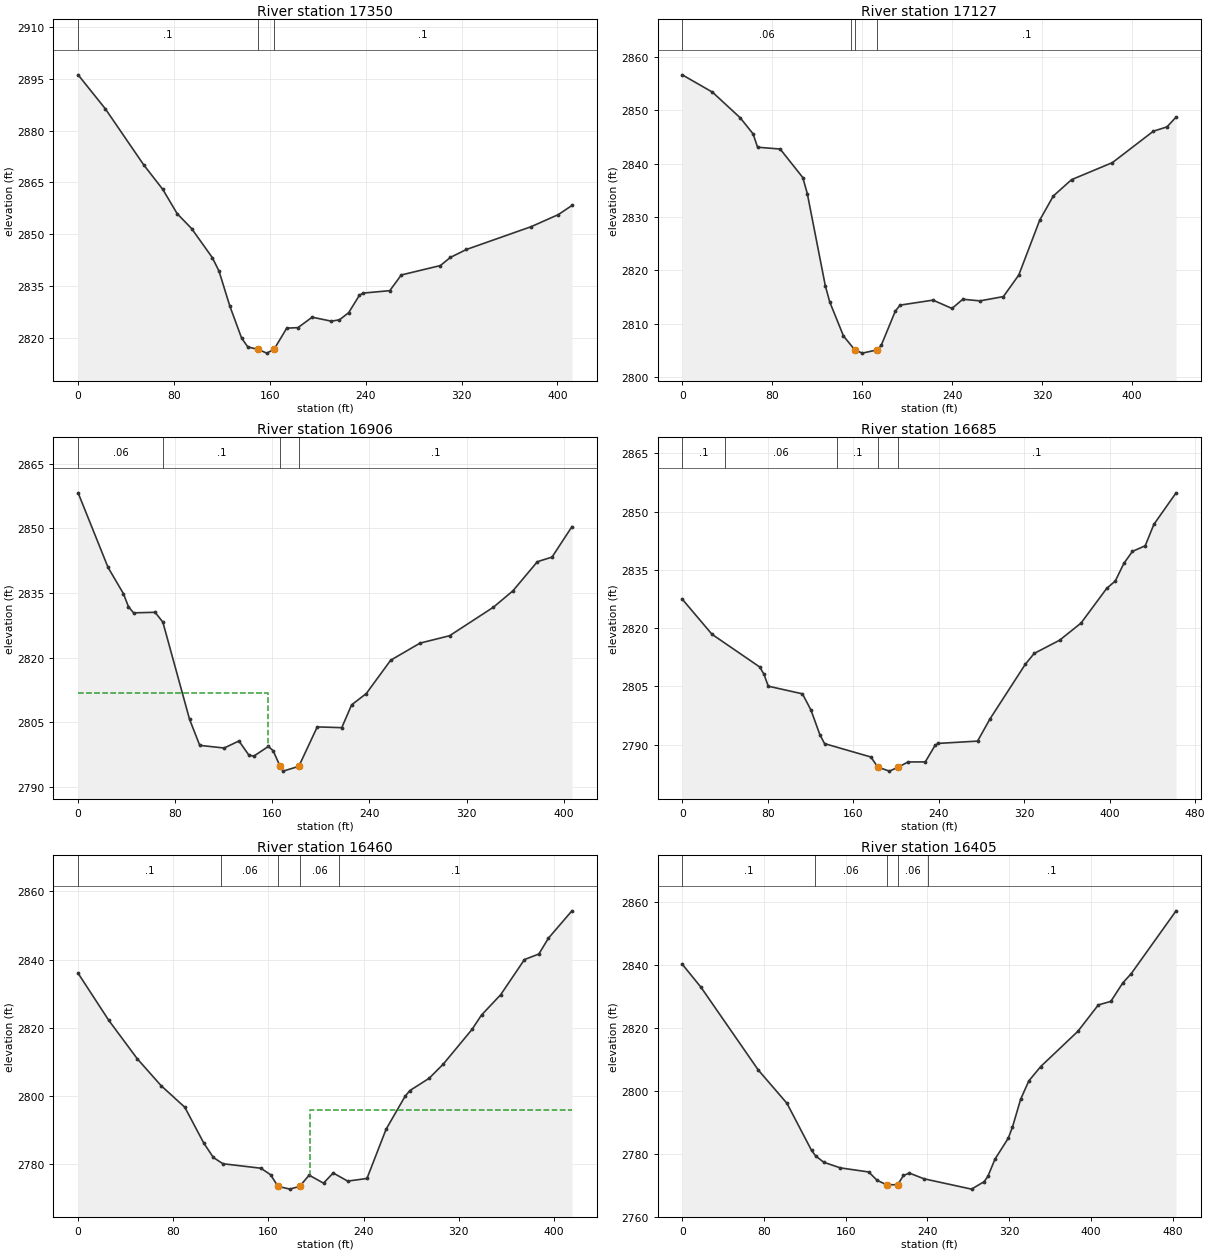
Type RM Length L Ch R = 1 ,17350   ,223,223,223
XS GIS Cut Line= 4
2255678.59779273565830.5200354262255677.01380517565939.638701758
2255780.34082866566003.9192765252255952.47346143566060.752004095
#Sta/Elev= 30
       0 2896.16    22.7 2886.34    54.7 2870.13    70.7 2862.99    82.7 2855.96
    94.7 2851.68     112 2843.26   117.6 2839.35   126.6 2829.25   136.4 2820.01
   141.6 2817.42   149.9 2816.73   157.5 2815.62  163.552816.735   174.1 2822.85
   183.5    2823   195.3 2826.02   211.3 2824.87   218.1 2825.26   225.8 2827.33
   234.8  2832.4     238    2833   260.1  2833.7   269.7 2838.24   302.3 2840.96
   310.7 2843.33   324.1 2845.62   378.1 2852.22   400.7  2855.7   412.1 2858.35
#Mann= 3 ,-1,0
       0      .1       0   149.9    .045       0  163.55      .1       0
Bank Sta=149.9,163.55
XS Rating Curve= 0 ,0
Exp/Cntr=0.3,0.1

Type RM Length L Ch R = 1 ,17127   ,221.2,221.2,221.2
XS GIS Cut Line= 4
2255417.33533319566116.6311950052255556.60036755566127.421106332
2255689.93743067566168.6742223332255848.17135146566192.205656353
#Sta/Elev= 30
       0 2856.62    26.9 2853.37    51.6 2848.56      63 2845.56      67 2843.06
    87.1 2842.72   107.2 2837.38   111.2 2834.39   127.2 2817.15   131.2 2814.06
   143.4  2807.7   153.5 2805.09   160.2 2804.49  173.222805.094   176.9 2805.92
   189.5 2812.36   193.7 2813.48     223 2814.42   239.9 2812.86   249.5 2814.58
   264.8 2814.28   285.6 2815.08   299.3 2819.12   317.9 2829.39     330 2833.92
   346.2 2836.98   382.6 2840.18     419 2846.06   431.1 2846.87   439.2  2848.7
#Mann= 4 ,-1,0
       0     .06       0  149.68      .1       0   153.5    .045       0
  173.22      .1       0
Bank Sta=153.5,173.22
XS Rating Curve= 0 ,0
Exp/Cntr=0.3,0.1

Type RM Length L Ch R = 1 ,16906   ,220.6,220.6,220.6
XS GIS Cut Line= 4
2255396.65735814566313.0982977192255490.89658864566343.019111519
   2255612.19462566359.4591124682255796.49265569 566381.02159216
#Sta/Elev= 30
       0 2858.27    24.7 2840.92    37.3 2834.86    41.5  2831.8    45.7 2830.38
    63.4 2830.51    69.8 2828.24    91.8 2805.65   100.2 2799.59   120.3 2798.97
   132.5 2800.61   140.5 2797.39   144.6 2797.06   156.7 2799.33   160.7 2798.34
  166.382794.716   168.8  2793.6  181.822794.713     197 2803.88   217.2  2803.7
   225.3    2809   237.4 2811.63   257.5 2819.38   281.7 2823.35     306 2825.06
   342.1 2831.69   358.2  2835.5   378.3 2842.26   390.4 2843.34   406.8 2850.41
#Mann= 4 ,-1,0
       0     .06       0      70      .1       0  166.38    .045       0
  181.82      .1       0
#XS Ineff= 2 , 0
          156.32 2811.84
Permanent Ineff=
       F       F
Bank Sta=166.38,181.82
XS Rating Curve= 0 ,0
Exp/Cntr=0.3,0.1

Type RM Length L Ch R = 1 ,16685   ,225.5,225.5,225.5
XS GIS Cut Line= 4
 2255327.6946051566590.3414240682255452.24344251566588.139478043
2255599.26397473566526.0969026782255777.00116121566537.137468028
#Sta/Elev= 30
       0 2827.47    27.8 2818.43    72.5    2810    76.5 2808.11    80.5 2805.06
   112.5 2803.09   120.5  2798.9   128.8 2792.58   133.2 2790.27   176.6 2786.82
  183.032784.216   193.9 2783.19  202.182784.217   211.3 2785.55   227.5 2785.57
   236.7 2789.86   239.7 2790.33   276.4 2790.92   287.9 2796.58   321.1 2810.71
   329.4 2813.49   353.2  2816.9   373.2  2821.3   397.3 2830.25   405.3 2832.14
   413.3 2836.66   421.3 2839.75   433.3 2841.21   441.4 2846.71   462.2 2854.84
#Mann= 5 ,-1,0
       0      .1       0      40     .06       0  144.57      .1       0
  183.03    .045       0  202.18      .1       0
Bank Sta=183.03,202.18
XS Rating Curve= 0 ,0
Exp/Cntr=0.3,0.1

Type RM Length L Ch R = 1 ,16460   ,54.4,54.4,54.4
XS GIS Cut Line= 4
2255342.44602475566773.730202279 2255502.1080436566775.471896973
2255588.54761992566761.7299478982255755.90196075566748.400485647
#Sta/Elev= 30
       0 2835.99    25.7 2822.24    49.7 2810.96    69.7 2803.09    89.7 2796.74
   105.7 2786.21   113.7 2782.03   121.7  2780.2   153.7 2778.88   161.8 2776.97
     168 2773.59     178 2772.76  186.26 2773.59   194.2 2776.85   206.3 2774.51
   214.4  2777.5   226.6 2775.11   242.8 2775.88   258.9 2790.32   274.9 2799.98
   278.9 2801.64     295 2805.21     307  2809.4   331.1 2819.54   339.1 2823.76
   355.2 2829.71   375.2 2840.01   387.3 2841.63   395.3 2846.25   415.1 2854.28
#Mann= 5 ,-1,0
       0      .1       0     120     .06       0     168    .045       0
  186.26     .06       0  219.67      .1       0
#XS Ineff= 2 , 0
                          195.31         2795.86
Permanent Ineff=
       F       F
Bank Sta=168,186.26
XS Rating Curve= 0 ,0
Exp/Cntr=0.3,0.1

Type RM Length L Ch R = 1 ,16405   ,54.3,54.3,54.3
XS GIS Cut Line= 6
2255333.79871365566825.4367094022255523.53922331566817.163489912
2255557.33528043 566839.059526922255567.80729813566854.767553469
2255573.99530859566881.8995993272255780.17462503566869.460732971
#Sta/Elev= 30
       0 2840.32    18.4 2832.96    74.4 2806.66   102.5 2796.05   126.6 2781.05
   130.6  2779.3   138.6 2777.28   154.8 2775.49   182.6 2774.19   190.7 2771.55
   200.1 2770.12  210.842770.127   216.6 2773.08   222.4 2773.83   236.7 2772.02
   283.2 2768.73   295.6 2771.11   299.2 2772.78   306.2 2778.28   319.2 2784.94
   323.3 2788.47   331.3 2797.32   339.3 2803.17     351 2807.76   387.4 2818.98
   407.4 2827.37   419.6 2828.48   431.4  2834.4   439.5 2837.28   483.5 2857.31
#Mann= 5 ,-1,0
       0      .1       0     130     .06       0   200.1    .045       0
  210.84     .06       0  240.28      .1       0
Bank Sta=200.1,210.84
XS Rating Curve= 0 ,0
Exp/Cntr(USF)=0,0
Exp/Cntr=0.3,0.1

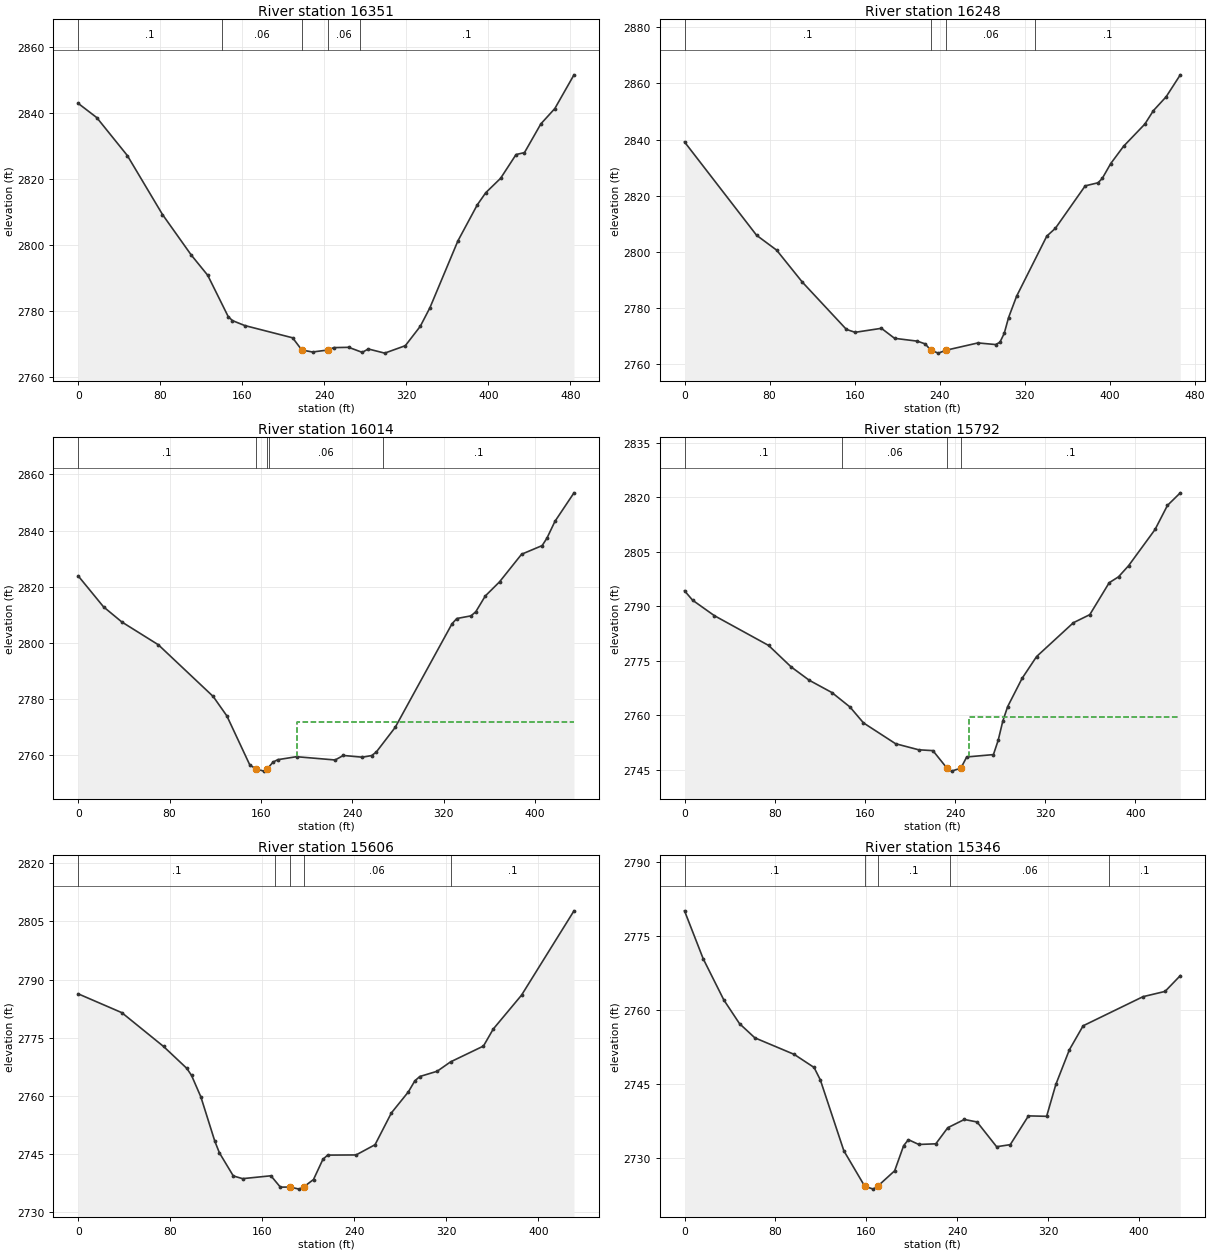
Type RM Length L Ch R = 1 ,16351   ,102.4,102.4,102.4
XS GIS Cut Line= 6
2255322.07056027566865.5528947842255511.81106993566857.279675293
2255545.60712706566879.1757123012255556.07914475 566894.88373885
2255562.26715521566922.0157847082255768.44647165566909.576918352
#Sta/Elev= 30
       0 2842.78    18.1 2838.47    47.9 2826.98    82.2  2809.1   110.3  2796.8
   126.3 2790.69   146.3 2778.16   150.4 2776.96   162.3 2775.47   209.1 2771.74
  218.062768.051   228.5 2767.44  243.652768.057   249.2 2768.77   263.8 2768.86
     277 2767.33   282.9 2768.36   298.9  2767.1     319 2769.35   333.6 2775.23
     343 2780.86   370.3 2801.12   389.2 2812.04   397.5 2815.73   411.9 2820.07
     427 2827.28   435.2 2827.86   451.2 2836.57   464.8 2841.21   483.5 2851.43
#Mann= 5 ,-1,0
       0      .1       0     140     .06       0  218.06    .045       0
  243.65     .06       0  274.75      .1       0
Bank Sta=218.06,243.65
XS Rating Curve= 0 ,0
Exp/Cntr(USF)=0,0
Exp/Cntr=0.3,0.1

Type RM Length L Ch R = 1 ,16248   ,234.4,234.4,234.4
XS GIS Cut Line= 4
 2255336.5930451567010.112499896 2255481.8525283566999.710073364
2255630.76604294566962.2962455862255797.42042147566952.972049138
#Sta/Elev= 30
       0 2839.16    67.8 2805.85    86.6 2800.57   110.8 2789.15   152.2  2772.3
   160.4 2771.26   185.1 2772.69   197.5 2769.12   218.9 2768.11   226.4 2767.11
  231.462764.887   238.6 2763.84  246.012764.888   275.9 2767.48   292.4  2766.9
   296.5  2767.7   300.6 2770.91   304.6 2776.45   312.2 2784.13   340.6 2805.57
   348.7 2808.37   376.7 2823.49   388.7 2824.58   392.7 2826.12   400.7 2831.44
   412.8 2837.62   432.8 2845.53   440.8 2850.31   452.8 2855.26   466.1 2863.08
#Mann= 4 ,-1,0
       0      .1       0  231.46    .045       0  246.01     .06       0
  329.17      .1       0
Bank Sta=231.46,246.01
XS Rating Curve= 0 ,0
Exp/Cntr=0.3,0.1

Type RM Length L Ch R = 1 ,16014   ,222,222,222
XS GIS Cut Line= 4
2255401.99953068567210.2024912762255549.04660893567211.083033763
2255656.33630672567187.1142071852255826.99490397567139.422032626
#Sta/Elev= 30
       0 2823.83    22.2 2812.81    38.2 2807.43    70.2  2799.3   118.2  2780.9
   130.2 2773.97   150.3 2756.49   155.8 2755.07   162.6 2754.31  165.432755.073
   170.7 2757.55   174.8 2758.39   191.2 2759.45     225 2758.28   232.2 2759.89
   248.9 2759.27     257 2759.86     261 2761.08   277.6 2769.89   327.4 2806.81
   331.6 2808.66     344 2809.61   348.2 2811.07   356.5 2816.68     369 2821.72
   388.3 2831.55   406.3 2834.63   410.5 2837.27   417.5 2843.25   434.2 2853.42
#Mann= 5 ,-1,0
       0      .1       0   155.8    .045       0  165.43      .1       0
  167.05     .06       0  266.98      .1       0
#XS Ineff= 2 , 0
                          191.34         2771.66
Permanent Ineff=
       F       F
Bank Sta=155.8,165.43
XS Rating Curve= 0 ,0
Exp/Cntr=0.3,0.1

Type RM Length L Ch R = 1 ,15792   ,186.3,186.3,186.3
XS GIS Cut Line= 4
2255429.78934929567404.6416005642255602.94403877567417.597889646
2255708.64736168 567390.029992032255854.94003913567333.069976409
#Sta/Elev= 30
       0  2794.3     7.2  2791.7    26.5 2787.45    74.6 2779.26    94.6 2773.35
   110.7 2769.67   130.8 2766.29   146.8 2762.32   158.8 2757.94   187.3 2752.21
   207.8 2750.54   220.4 2750.31   232.8 2745.52   236.9 2744.67   245.2 2745.49
   250.4 2748.57   274.1 2749.22   278.3 2753.14   282.4 2758.42   286.7 2762.41
   299.5 2770.18   312.4  2776.2     345  2785.5   359.6 2787.73   376.8 2796.51
   385.1 2798.14     394 2801.19   417.5 2811.16   428.5 2817.79   439.9 2821.25
#Mann= 4 ,-1,0
       0      .1       0     140     .06       0   232.8    .045       0
   245.2      .1       0
#XS Ineff= 2 , 0
                          251.99         2759.66
Permanent Ineff=
       F       F
Bank Sta=232.8,245.2
XS Rating Curve= 0 ,0
Exp/Cntr=0.3,0.1

Type RM Length L Ch R = 1 ,15606   ,259.2,259.2,259.2
XS GIS Cut Line= 4
2255498.68550748 567571.782087672255648.61437251567593.126821194
2255757.68376735567566.6725050022255890.89245622 567465.64505378
#Sta/Elev= 30
       0 2786.34    37.9 2781.49    74.2 2772.77    94.4 2767.13    98.5 2765.31
   106.6 2759.78   118.7 2748.38   122.7 2745.37   134.8  2739.4   142.9  2738.7
   167.5 2739.44   175.7 2736.51   183.9 2736.54   192.1    2736  195.94 2736.55
   204.5 2738.48   212.7  2743.7   216.8 2744.77   241.5 2744.81     258 2747.45
   272.2 2755.65   286.9 2761.05   292.6 2763.92   296.9 2765.03     312 2766.39
   323.6  2768.8   352.2 2772.88   360.7 2777.26   385.3    2786   430.9 2807.74
#Mann= 5 ,-1,0
       0      .1       0  171.44     .06       0   183.9    .045       0
  195.94     .06       0  323.67      .1       0
Bank Sta=183.9,195.94
XS Rating Curve= 0 ,0
Exp/Cntr=0.3,0.1

Type RM Length L Ch R = 1 ,15346   ,234.9,234.9,234.9
XS GIS Cut Line= 4
2255427.97368988567711.6846780322255559.57172009567770.033274371
2255649.09608409567849.2498263732255821.53398972 567858.28274206
#Sta/Elev= 30
       0 2780.17    16.4 2770.45    34.6 2762.05    48.4 2757.24    61.9 2754.35
    96.5 2750.99     114 2748.33   119.5  2745.8   140.2 2731.39  158.572724.187
   166.1  2723.6  169.992724.198   184.9 2727.33   192.8 2732.44     197 2733.65
   206.1 2732.68   221.1 2732.81   231.6 2736.08   246.2 2737.76   257.4 2737.25
   274.6 2732.22   286.6 2732.64   302.6 2738.49   318.6  2738.4   326.7 2744.88
   338.6 2751.92   350.7  2756.8   403.4 2762.72   422.8 2763.79   436.2    2767
#Mann= 5 ,-1,0
       0      .1       0  158.57    .045       0  169.99      .1       0
  233.95     .06       0  373.49      .1       0
Bank Sta=158.57,169.99
XS Rating Curve= 0 ,0
Exp/Cntr=0.3,0.1

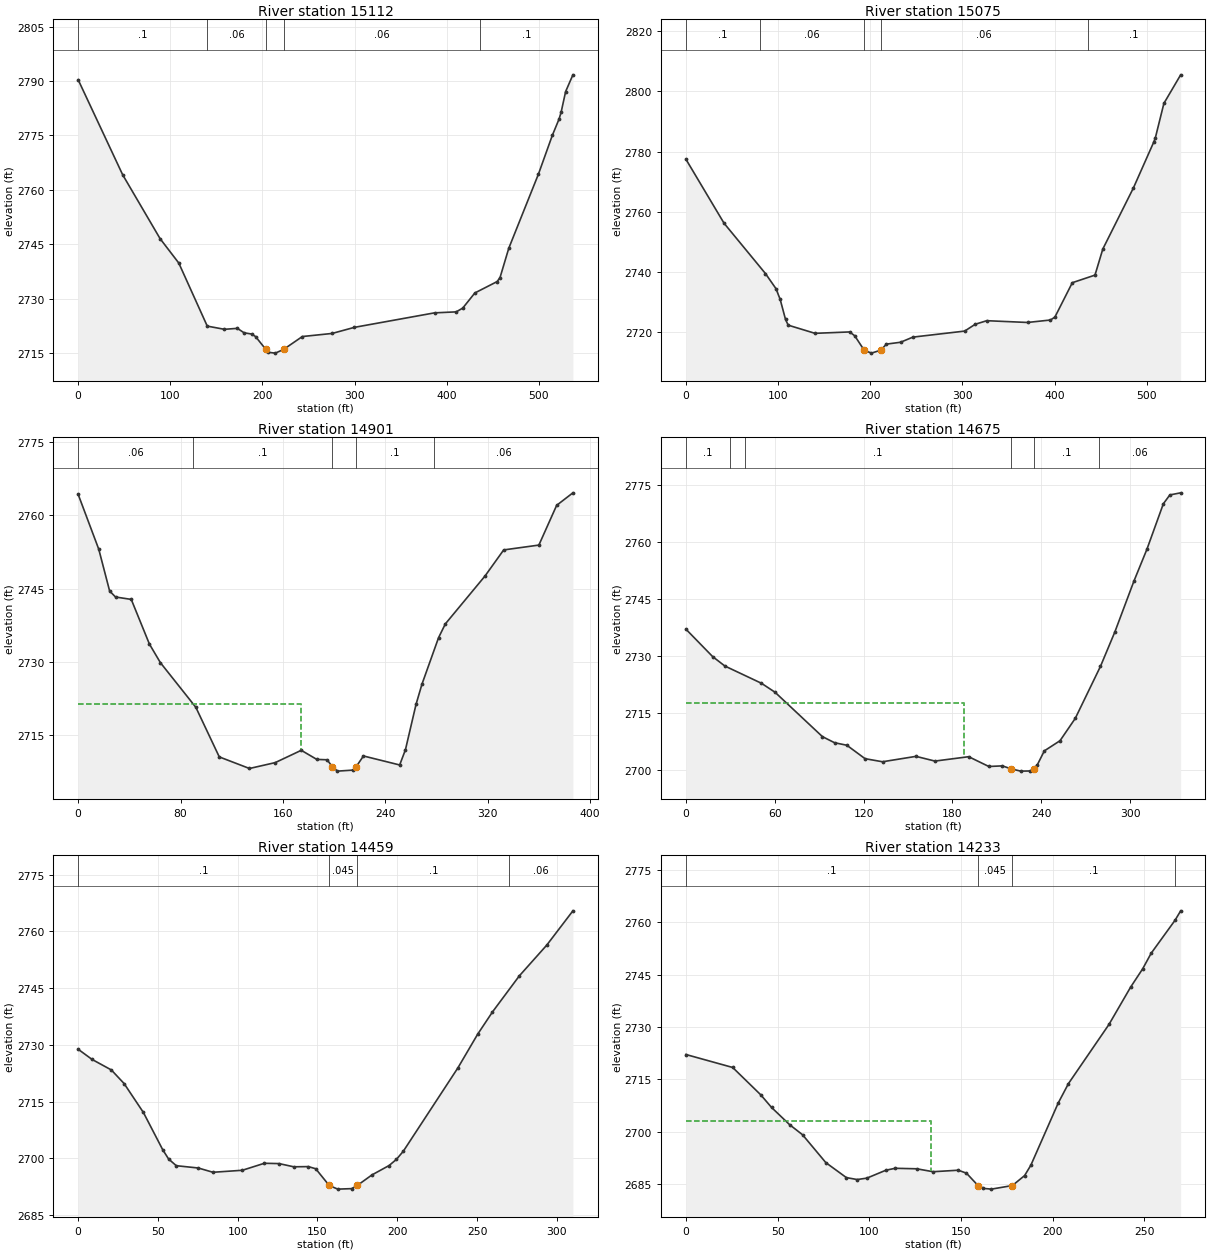
Type RM Length L Ch R = 1 ,15112   ,37,37,37
XS GIS Cut Line= 6
2255214.30575962567856.3405989422255332.66086855567931.384036326
2255365.10360882567927.5067252272255432.11906487567948.221377293
 2255524.5793422567942.2982298282255632.24601426 568111.99631495
#Sta/Elev= 30
       0 2790.35    48.3 2764.18    88.9 2746.59   109.2 2739.87   140.1  2722.5
   158.7 2721.62   172.8 2721.88   180.1 2720.65   188.3 2720.32   192.5 2719.62
  203.72 2716.07   205.5 2715.31     214 2715.06  222.852716.069   243.3 2719.63
   275.6 2720.48   299.8 2722.16   386.7 2726.15   410.2 2726.42   417.3 2727.45
   430.5 2731.63   454.7 2734.77   457.8 2735.86   467.3 2743.94   499.5 2764.36
   514.6 2775.05   521.9 2779.54   524.1 2781.39     529 2787.09   536.9  2791.7
#Mann= 5 ,-1,0
       0      .1       0     140     .06       0  203.72    .045       0
  222.85     .06       0  435.95      .1       0
Bank Sta=203.72,222.85
XS Rating Curve= 0 ,0
Exp/Cntr=0.3,0.1

Type RM Length L Ch R = 1 ,15075   ,173.6,173.6,173.6
XS GIS Cut Line= 6
2255199.30081373567888.8718644752255317.65592266567963.915301859
2255350.09866293 567960.037990762255417.11411899567980.752642826
2255509.57439631567974.8294953612255617.24106838568144.527580482
#Sta/Elev= 30
       0 2777.44    41.4 2756.12    86.3 2739.38    97.7 2734.36   102.3 2730.75
   108.1 2724.08     111 2722.19   140.1 2719.47   177.7 2719.94   183.2 2718.65
  193.442713.853   201.3 2712.88  211.312713.851   217.6 2715.88   232.9  2716.5
   246.3 2718.21   302.5 2720.22     314  2722.5   326.5 2723.68   370.7 2723.09
   395.6 2723.91   400.4 2724.88   419.3 2736.33   443.9 2738.86   452.4 2747.54
   485.6 2767.88   507.6  2783.1   509.3 2784.42   518.7 2796.05   536.9 2805.55
#Mann= 5 ,-1,0
       0      .1       0      80     .06       0  193.44    .045       0
  211.31     .06       0  435.95      .1       0
Bank Sta=193.44,211.31
XS Rating Curve= 0 ,0
Exp/Cntr=0.3,0.1

Type RM Length L Ch R = 1 ,14901   ,225.5,225.5,225.5
XS GIS Cut Line= 4
2255105.60265407568017.0399876452255186.97788074568094.613547354
2255330.80209895568117.1088173672255443.50401663568179.325051946
#Sta/Elev= 30
       0 2764.27    16.1 2753.05    24.6  2744.5    29.2 2743.27    41.5 2742.78
    55.7 2733.64    64.3 2729.83      92  2720.7   110.3 2710.56   133.9 2708.19
     154 2709.39   174.4 2711.91   186.5 2710.05   194.6 2709.97  198.542708.586
   202.7 2707.65   214.9 2707.86  217.382708.588     223 2710.75   251.3 2708.91
   255.8 2712.02   264.1 2721.32   268.7 2725.42   281.7 2734.95     287 2737.77
   317.9 2747.53   332.6  2752.9   360.1 2753.89     374 2762.02   386.7 2764.58
#Mann= 5 ,-1,0
       0     .06       0      90      .1       0  198.54    .045       0
  217.38      .1       0     278     .06       0
#XS Ineff= 2 , 0
          174.15 2721.36
Permanent Ineff=
       F       F
Bank Sta=198.54,217.38
XS Rating Curve= 0 ,0
Exp/Cntr=0.3,0.1

Type RM Length L Ch R = 1 ,14675   ,216.3,216.3,216.3
XS GIS Cut Line= 4
2255060.89903773568091.6590756322255092.36687331568219.785061919
2255168.64305159568294.777527627 2255231.1441247568366.684868739
#Sta/Elev= 30
       0  2737.1      18 2729.91    26.3 2727.42      51 2722.89    60.2 2720.53
    92.2 2708.87   100.4 2707.27   108.7 2706.61     121 2703.08   132.8 2702.27
   155.4 2703.69   168.2 2702.45     191  2703.6   204.6 2701.03   213.8 2701.19
   219.5 2700.42   226.1 2699.81   232.6 2699.85  235.062700.418   237.4 2701.49
   242.1 2705.13   252.7  2707.8     263 2713.67     280 2727.31   289.8 2736.43
   302.6  2749.7   311.4 2758.09   322.5 2770.04   326.9 2772.36   334.2 2772.91
#Mann= 6 ,-1,0
       0      .1       0      30     .06       0      40      .1       0
   219.5    .045       0  235.06      .1       0   278.9     .06       0
#XS Ineff= 2 , 0
          187.51 2717.78
Permanent Ineff=
       F       F
Bank Sta=219.5,235.06
XS Rating Curve= 0 ,0
Exp/Cntr=0.3,0.1

Type RM Length L Ch R = 1 ,14459   ,225.7,225.7,225.7
XS GIS Cut Line= 4
2254897.51288969568172.5567318682254904.69955287568230.334176852
2254974.76803281568353.814507612 2255013.7829491 568456.52965139
#Sta/Elev= 30
       0 2728.83     8.7 2726.14    20.8 2723.35    28.8 2719.75    40.9 2712.09
      53 2702.24    56.7 2699.78    61.5 2698.01    75.3  2697.4    84.5 2696.27
   102.9  2696.8   116.7 2698.65   125.9 2698.57   135.1 2697.72   144.3 2697.77
   148.9  2697.2  157.362692.776   162.7 2691.81   171.4 2691.94  174.962692.777
   184.1 2695.56   194.9 2698.06   199.5 2699.69   203.8 2701.84     238 2723.89
   250.4 2732.81   259.7 2738.71   276.5 2748.24   293.7 2756.38   310.1 2765.46
#Mann= 4 ,-1,0
       0      .1       0  157.36    .045       0  174.96      .1       0
   270.2     .06       0
Bank Sta=157.36,174.96
XS Rating Curve= 0 ,0
Exp/Cntr=0.3,0.1

Type RM Length L Ch R = 1 ,14233   ,223.9,223.9,223.9
XS GIS Cut Line= 4
2254696.32065395568281.0922903682254722.81010807568357.031160653
2254772.50798836 568451.052092672254813.69152533 568523.13447346
#Sta/Elev= 30
       0 2722.13    25.5 2718.42    40.8  2710.6    46.7 2706.98    56.5 2702.08
    63.6 2699.17    76.3  2691.2    87.5 2686.92    93.4 2686.36    98.7 2686.77
     109 2689.02   114.1 2689.58   125.8 2689.44   134.8  2688.6   148.5 2689.03
     153 2688.18  159.272684.651     162 2683.84   166.6 2683.62  178.04 2684.65
   184.7  2687.5   188.1 2690.46     203 2708.23   208.6 2713.81   230.7 2730.73
   242.5  2741.4   249.1 2746.66   253.7 2751.09   266.7 2760.51   269.8 2763.23
#Mann= 4 ,-1,0
       0      .1       0  159.27    .045       0  178.04      .1       0
  266.77     .06       0
#XS Ineff= 2 , 0
          133.43  2703.1
Permanent Ineff=
       F       F
Bank Sta=159.27,178.04
XS Rating Curve= 0 ,0
Exp/Cntr=0.3,0.1

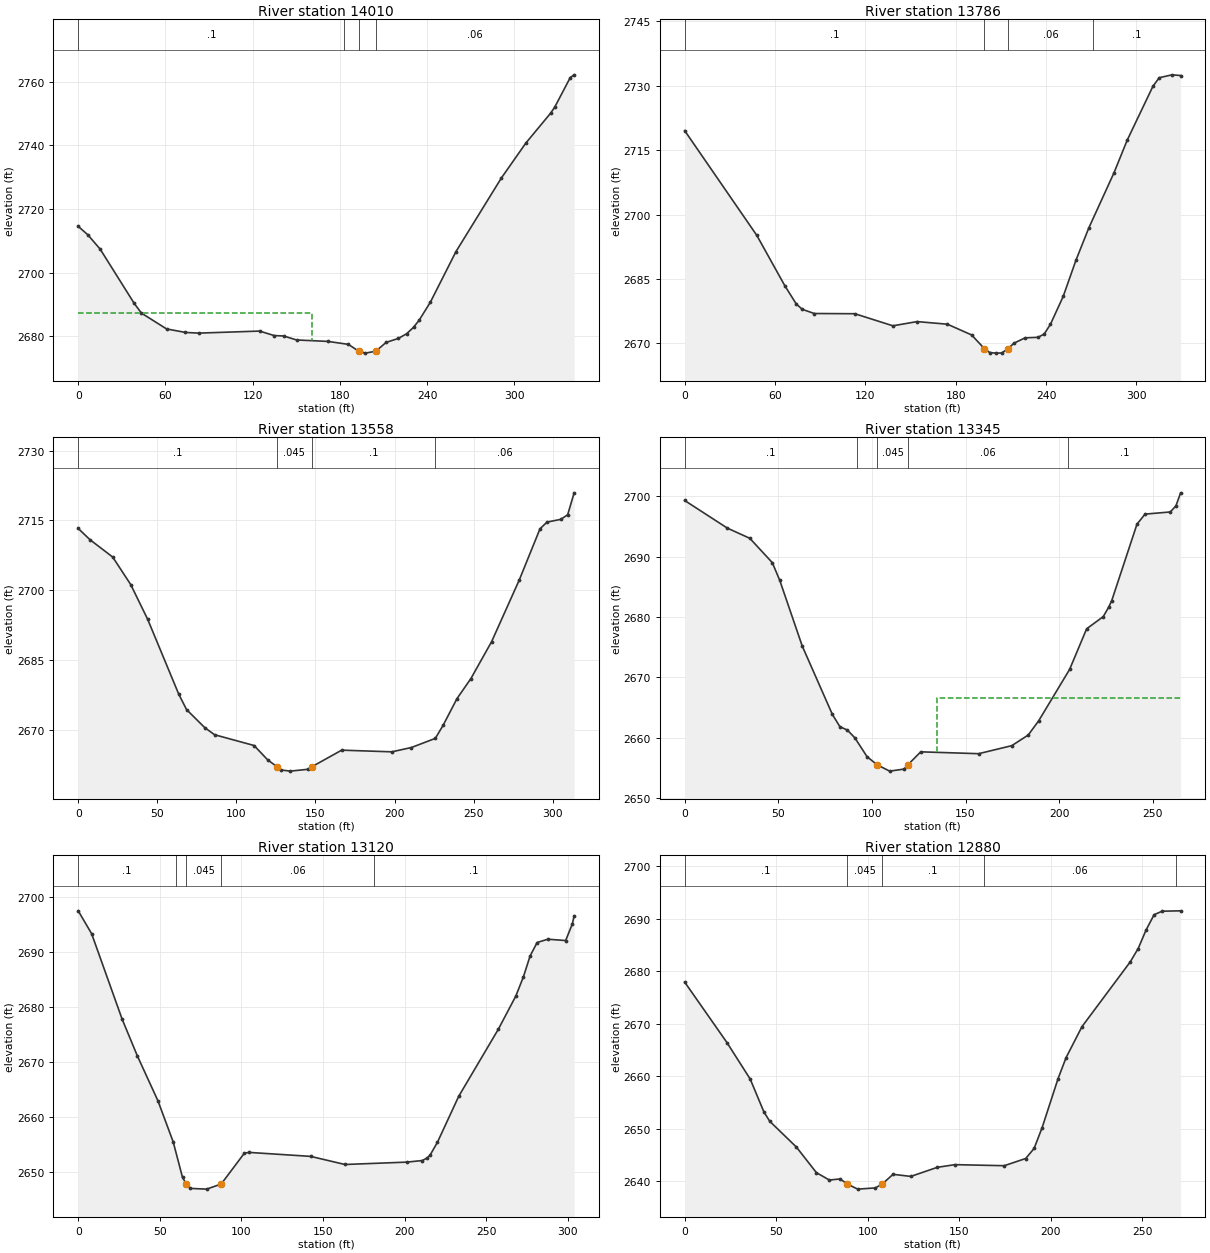
Type RM Length L Ch R = 1 ,14010   ,223.2,223.2,223.2
XS GIS Cut Line= 4
2254446.07057835568374.1734663672254477.61066064568416.944604022
2254582.50309245568549.9762235262254665.09686941568635.100921938
#Sta/Elev= 30
       0 2714.54     6.5 2711.94    15.1 2707.39    38.5 2690.36    43.5 2687.28
    60.8 2682.31    73.8 2681.21    83.1    2681   124.8 2681.64   134.8 2680.23
   141.3  2680.1   150.2 2678.85   171.9 2678.39   185.9 2677.46     193 2675.31
   197.5 2674.71  204.762675.312   211.8 2678.07   220.3 2679.34     226 2680.82
   230.7 2682.83   234.5 2685.02   242.2 2690.65   259.9 2706.62   291.1 2729.72
     308 2740.73     325  2750.1   327.8 2751.97   338.5 2761.28   341.2 2762.15
#Mann= 4 ,-1,0
       0      .1       0  183.14     .06       0     193    .045       0
  204.76     .06       0
#XS Ineff= 2 , 0
          160.67 2687.29
Permanent Ineff=
       F       F
Bank Sta=193,204.76
XS Rating Curve= 0 ,0
Exp/Cntr=0.3,0.1

Type RM Length L Ch R = 1 ,13786   ,228.3,228.3,228.3
XS GIS Cut Line= 4
2254327.60308225568419.9137204482254353.86594481568489.092925709
2254368.95797695568655.7459453472254399.07852758568738.457527398
#Sta/Elev= 30
       0 2719.52    47.9 2695.15    66.5 2683.44    74.1 2679.19    78.1 2677.93
    86.1 2676.96     113 2676.91   138.3  2674.1   154.4 2675.08   174.5 2674.47
   190.6 2671.97  198.992668.805   202.6 2667.88   206.6 2667.74   210.6 2667.78
  214.862668.804   218.7 2670.05   226.1  2671.3   234.7 2671.42   238.8 2672.19
   242.9 2674.43   251.4 2680.93   259.9 2689.38   268.4 2696.86   285.2 2709.75
   293.9 2717.29     311 2729.84   315.2 2731.84   323.7 2732.51   329.4 2732.35
#Mann= 4 ,-1,0
       0      .1       0  198.99    .045       0  214.86     .06       0
  271.33      .1       0
Bank Sta=198.99,214.86
XS Rating Curve= 0 ,0
Exp/Cntr=0.3,0.1

Type RM Length L Ch R = 1 ,13558   ,212.7,212.7,212.7
XS GIS Cut Line= 4
2254077.38347185568517.5784071362254117.30259741568572.990979515
2254172.08139326568720.663363363 2254207.7813525568800.916859457
#Sta/Elev= 30
       0 2713.27     7.4 2710.86    21.8 2707.12    33.2  2701.2    43.9 2693.75
    63.6 2677.61    68.5 2674.32      80 2670.44    86.2 2668.91   111.2 2666.59
   119.7 2663.54  125.832661.986   128.2 2661.33   134.1 2661.08   145.4 2661.48
  147.552661.986   166.6 2665.59   198.3 2665.23   210.7 2666.16   225.8 2668.12
   230.7 2670.91   239.5 2676.67   248.3 2680.98   261.4 2688.92   278.9 2702.19
     292 2713.19   296.4 2714.63   305.2 2715.23   309.5 2716.22   313.6 2720.93
#Mann= 4 ,-1,0
       0      .1       0  125.83    .045       0  147.55      .1       0
   225.8     .06       0
Bank Sta=125.83,147.55
XS Rating Curve= 0 ,0
Exp/Cntr=0.3,0.1

Type RM Length L Ch R = 1 ,13345   ,225.2,225.2,225.2
XS GIS Cut Line= 4
2253939.77449786568622.3980347272253943.82268451568714.372740191
2253978.84365919568789.2480372942254018.37105176568870.256551503
#Sta/Elev= 30
       0  2699.3    22.8 2694.72    34.8 2693.03    46.8    2689    50.8 2686.05
    62.8 2675.17    78.9 2663.83    82.9 2661.81    86.9 2661.24    90.9 2659.96
    97.4 2656.84  102.782655.488   109.5 2654.44   117.2 2654.78   119.22655.488
   126.1 2657.64     157 2657.33   174.7 2658.66   183.5 2660.42   189.1 2662.79
   205.6  2671.3   214.7 2678.03   223.6 2680.06   226.5 2681.63   228.1  2682.7
   241.6 2695.38   245.9 2697.04   259.4  2697.4   262.4 2698.41   264.9 2700.57
#Mann= 5 ,-1,0
       0      .1       0   92.06     .06       0  102.78    .045       0
   119.2     .06       0  204.72      .1       0
#XS Ineff= 2 , 0
                          134.79         2666.56
Permanent Ineff=
       F       F
Bank Sta=102.78,119.2
XS Rating Curve= 0 ,0
Exp/Cntr=0.3,0.1

Type RM Length L Ch R = 1 ,13120   ,240.1,240.1,240.1
XS GIS Cut Line= 4
2253717.61452213568661.2920727212253738.39272628568718.858542795
2253822.07675839568850.8000827152253856.61872194 568929.91536989
#Sta/Elev= 30
       0 2697.43     8.2 2693.29    26.9 2677.78    36.3 2671.06    48.8 2662.99
    58.2  2655.5    63.9 2649.05    66.22647.878    68.7 2647.07    78.7 2646.94
    87.6 2647.87   101.8 2653.47   104.8  2653.6   142.4 2652.88   163.4 2651.41
   201.3 2651.84   210.8 2652.13   213.9 2652.63   215.5 2653.09     220 2655.41
   233.1 2663.79   257.3 2675.92   268.1 2681.99   272.7 2685.44   276.8 2689.23
   281.1 2691.68   287.7 2692.28   298.6 2692.04   302.7 2695.06   303.8 2696.53
#Mann= 5 ,-1,0
       0      .1       0      60     .06       0    66.2    .045       0
    87.6     .06       0   181.2      .1       0
Bank Sta=66.2,87.6
XS Rating Curve= 0 ,0
Exp/Cntr=0.3,0.1

Type RM Length L Ch R = 1 ,12880   ,163.7,163.7,163.7
XS GIS Cut Line= 4
 2253511.0088108568775.3327421422253531.58805406568835.709521979
2253601.55981187568938.8342756422253635.13614447569014.451480026
#Sta/Elev= 30
       0 2677.93    23.1 2666.42    35.8 2659.48    43.3 2653.22    46.5 2651.43
    61.1 2646.51      72 2641.65    79.1 2640.24    84.9 2640.45   88.992639.463
    94.6 2638.51   104.2 2638.74  107.932639.464   113.9 2641.33   123.6 2640.93
   138.1 2642.66   147.7 2643.17   174.7 2642.97   186.4 2644.34     191 2646.25
   195.4 2650.22   204.1 2659.54   208.5 2663.56   217.2 2669.46   243.5 2681.75
   247.9 2684.32   252.2 2687.84   256.6 2690.76     261 2691.43   271.1  2691.5
#Mann= 5 ,-1,0
       0      .1       0   88.99    .045       0  107.93      .1       0
  163.79     .06       0  268.41      .1       0
Bank Sta=88.99,107.93
XS Rating Curve= 0 ,0
Exp/Cntr=0.3,0.1

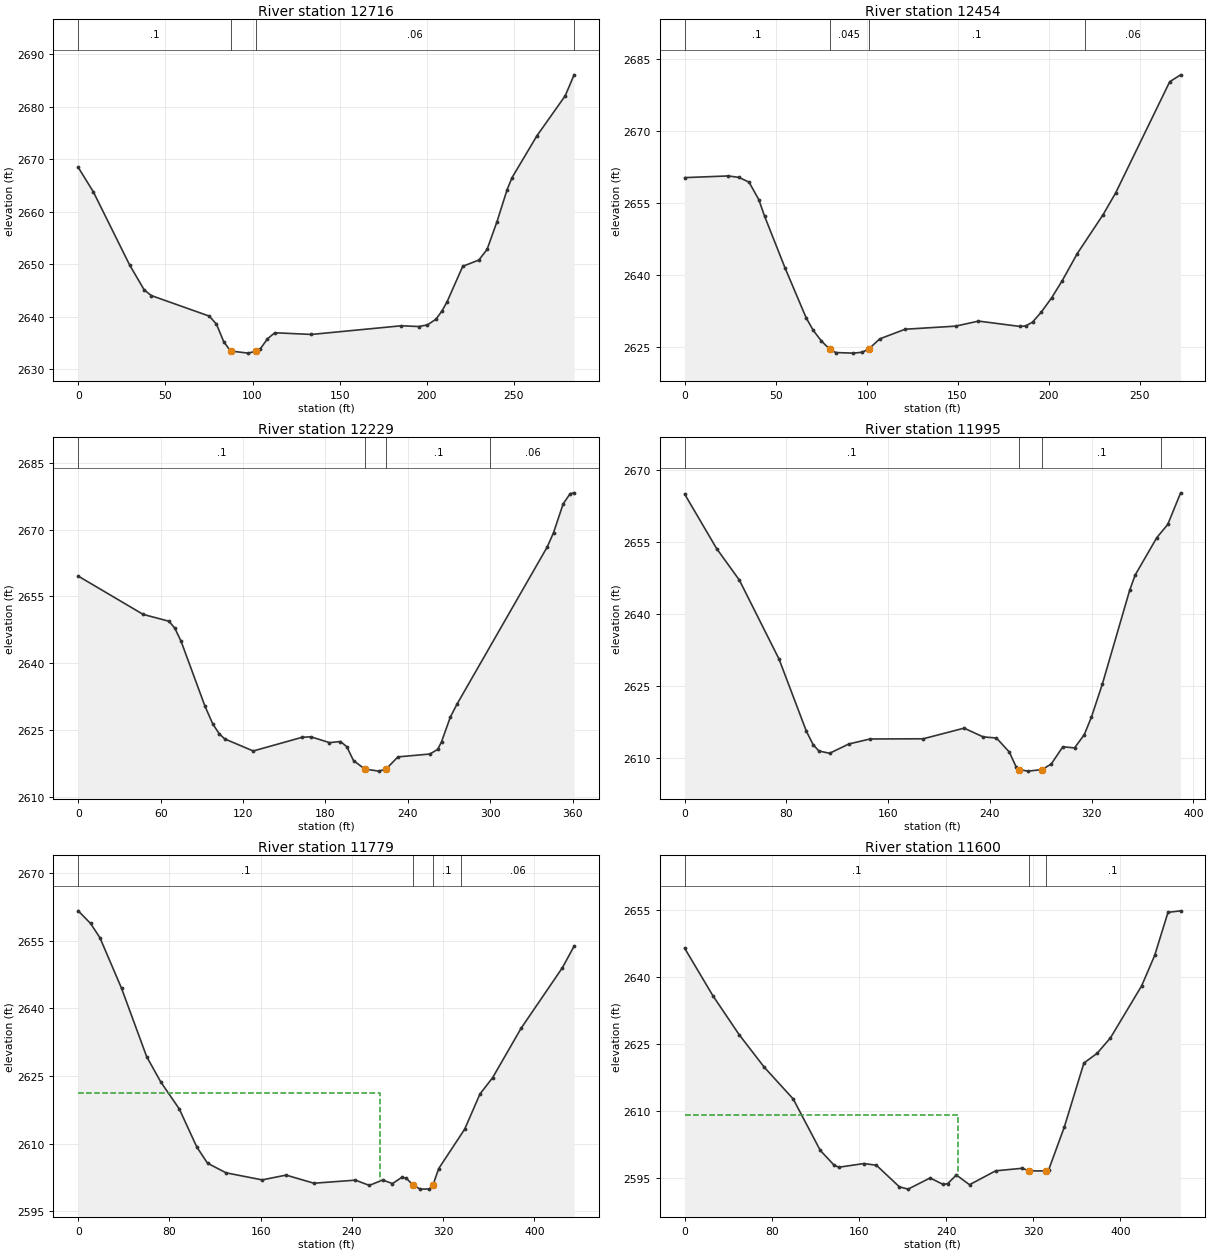
Type RM Length L Ch R = 1 ,12716   ,262.7,262.7,262.7
XS GIS Cut Line= 4
2253371.95962288568828.8048516182253393.72296749568906.244366894
2253413.97313522568971.5438654422253493.72768574569081.379470974
#Sta/Elev= 30
       0 2668.43     8.7 2663.75    29.5 2649.83    37.8 2645.12    41.9 2644.01
    75.2 2640.09    79.3 2638.57    83.5 2635.21   87.422633.443    97.5 2633.04
   102.2 2633.43   104.5 2633.87   108.6 2635.77   112.8 2636.92   133.8  2636.6
   185.4 2638.25   195.3 2638.11   200.3 2638.41   205.2 2639.49   208.8 2641.11
   211.7 2642.87   220.6 2649.57   229.9 2650.78   234.6 2652.81   240.3 2658.11
   246.1  2664.2   248.9 2666.47   263.2 2674.45   279.4 2682.05   284.5 2686.05
#Mann= 4 ,-1,0
       0      .1       0   87.42    .045       0   102.2     .06       0
  284.54      .1       0
Bank Sta=87.42,102.2
XS Rating Curve= 0 ,0
Exp/Cntr=0.3,0.1

Type RM Length L Ch R = 1 ,12454   ,224.6,224.6,224.6
XS GIS Cut Line= 4
2253130.99289273569020.2758185612253178.72929571569066.951758277
2253280.66047706569136.3097425592253336.19682579 569197.31812307
#Sta/Elev= 30
       0 2660.29      24 2660.64    29.9 2660.33    35.4 2659.34    40.8 2655.66
    43.9 2652.29    55.2 2641.48    66.8 2631.12    70.7 2628.52    75.2  2626.3
   79.672624.648      83 2623.92    92.7  2623.8    97.5 2623.98  101.16 2624.65
   107.2 2626.76   121.2 2628.77   148.9 2629.41   161.5 2630.46   184.5 2629.34
   187.5 2629.47   191.2 2630.24     196 2632.33   201.7 2635.29   207.5 2638.85
   215.8  2644.5     230  2652.6   236.9 2657.12   266.6 2680.22   272.6 2681.66
#Mann= 4 ,-1,0
       0      .1       0   79.67    .045       0  101.16      .1       0
  220.05     .06       0
Bank Sta=79.67,101.16
XS Rating Curve= 0 ,0
Exp/Cntr=0.3,0.1

Type RM Length L Ch R = 1 ,12229   ,234.3,234.3,234.3
XS GIS Cut Line= 4
2252879.13262042569152.2270411382252971.36702462569204.988010021
2253103.70967294569283.403125079 2253182.3723948569346.539944481
#Sta/Elev= 30
       0 2659.57    47.3 2650.95      66 2649.42    70.3 2647.87    74.9 2644.89
    92.3 2630.29      98 2626.29   102.6 2624.13   106.6 2622.96   127.4 2620.24
     163 2623.32   169.4 2623.43   182.9 2622.12   190.9 2622.37   195.5  2621.2
   200.4 2618.08   208.6 2616.18   218.8 2615.71  224.092616.172   232.7 2618.91
     256 2619.56   261.7  2620.6   264.5 2622.34   270.9 2627.89   275.7 2630.76
   341.4 2666.12     346 2669.34     353 2675.81   358.1 2678.11     361 2678.29
#Mann= 4 ,-1,0
       0      .1       0   208.6    .045       0  224.09      .1       0
  300.09     .06       0
Bank Sta=208.6,224.09
XS Rating Curve= 0 ,0
Exp/Cntr=0.3,0.1

Type RM Length L Ch R = 1 ,11995   ,216.1,216.1,216.1
XS GIS Cut Line= 4
2252713.61988099569334.9659686232252802.20602517569378.519159048
2252990.93162048569482.5100645212253061.62359695569509.662089316
#Sta/Elev= 30
       0 2664.98    25.1 2653.64      43 2647.06    74.2 2630.59    95.7 2615.55
     101 2612.77   105.5 2611.45   113.9 2610.97   129.1 2612.91   145.7 2613.95
   187.5 2613.99   219.7 2616.21   234.6 2614.39   245.1 2614.15   255.2 2611.24
   260.8 2608.01  262.952607.573   269.9 2607.25  280.892607.569   288.2 2608.74
   297.3 2612.33   306.5 2612.09   314.2 2614.87   319.8 2618.52   328.4 2625.42
   349.8  2644.9   354.1 2648.09   371.2 2655.92   379.8 2658.67   389.9 2665.25
#Mann= 4 ,-1,0
       0      .1       0  262.95    .045       0  280.89      .1       0
  374.19     .06       0
Bank Sta=262.95,280.89
XS Rating Curve= 0 ,0
Exp/Cntr=0.3,0.1

Type RM Length L Ch R = 1 ,11779   ,179,179,179
XS GIS Cut Line= 4
2252581.63485244569607.2467659762252696.36042629569633.324234373
2252891.84406038569665.6406350832253010.40668669569676.831069627
#Sta/Elev= 30
       0 2661.65    10.8 2658.86      19 2655.71      38 2644.47      60 2629.33
    72.3 2623.75    88.7 2617.69     104 2609.28   113.4 2605.69   129.6 2603.56
   161.3 2601.99   182.3 2603.05   206.7 2601.25   243.1 2601.93   255.3 2600.77
     267 2601.96   275.6 2601.17   283.7 2602.54   287.7 2602.38  293.432600.863
   299.9 2599.94     308 2599.98  311.112600.858   316.1 2604.49   338.9 2613.24
   352.3 2621.03   363.4 2624.65   388.4 2635.62   424.6 2649.04   434.9 2653.85
#Mann= 4 ,-1,0
       0      .1       0  293.43    .045       0  311.11      .1       0
  335.79     .06       0
#XS Ineff= 2 , 0
          264.84 2621.16
Permanent Ineff=
       F       F
Bank Sta=293.43,311.11
XS Rating Curve= 0 ,0
Exp/Cntr=0.3,0.1

Type RM Length L Ch R = 1 ,11600   ,262.3,262.3,262.3
XS GIS Cut Line= 4
 2252556.1032841569756.385069616 2252734.4700508569825.537389447
2252880.24007569569843.3978092682252995.68895491569863.488564252
#Sta/Elev= 30
       0 2646.39    25.8  2635.8    50.1 2627.01      73 2619.77    99.6 2612.65
   124.5 2601.12   137.4 2597.76   141.7 2597.36   164.5 2598.18     176  2597.8
   197.1 2592.97   205.1 2592.45   225.3 2594.95   237.3  2593.5   241.4 2593.67
   249.4 2595.62   261.5 2593.44   285.5 2596.55   309.9 2597.12  316.512596.529
   331.5 2596.53   334.1 2596.73   348.6 2606.41   366.5 2620.68   378.7 2622.88
   390.9 2626.33   419.5 2637.97   431.5 2644.79   443.7 2654.43   455.3 2654.77
#Mann= 3 ,-1,0
       0      .1       0  316.51    .045       0   331.5      .1       0
#XS Ineff= 2 , 0
          250.99 2608.99
Permanent Ineff=
       F       F
Bank Sta=316.51,331.5
XS Rating Curve= 0 ,0
Exp/Cntr=0.3,0.1