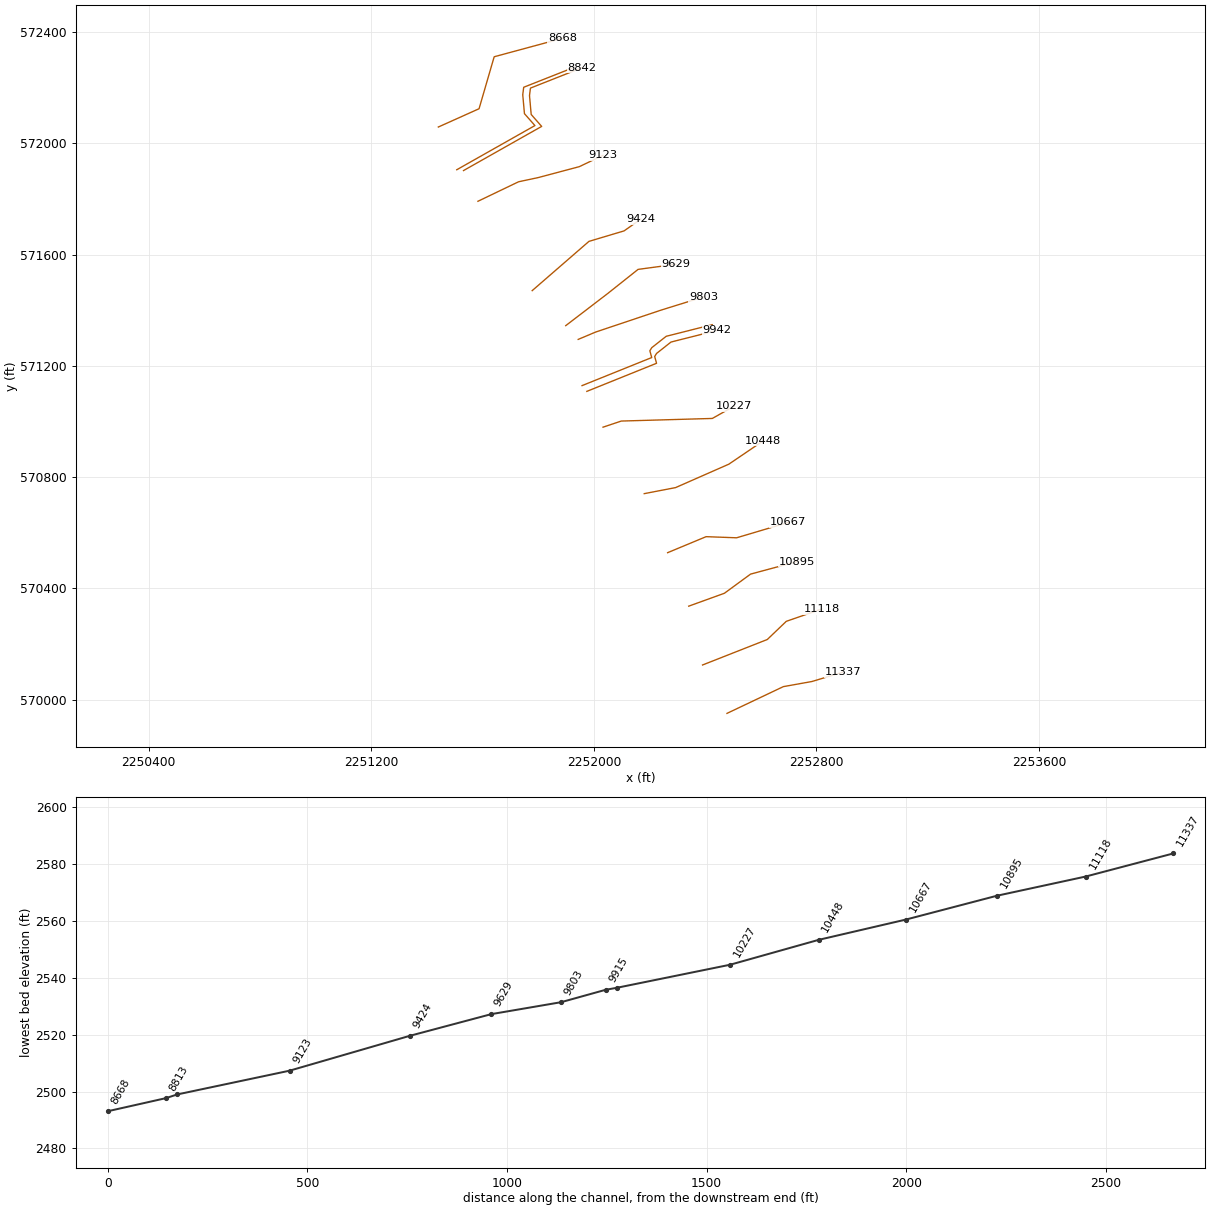
HEC-RAS study CONLEYRN.prj: CONLEYRN

--- CONLEYRN.g01 (geometry) --- (continued)

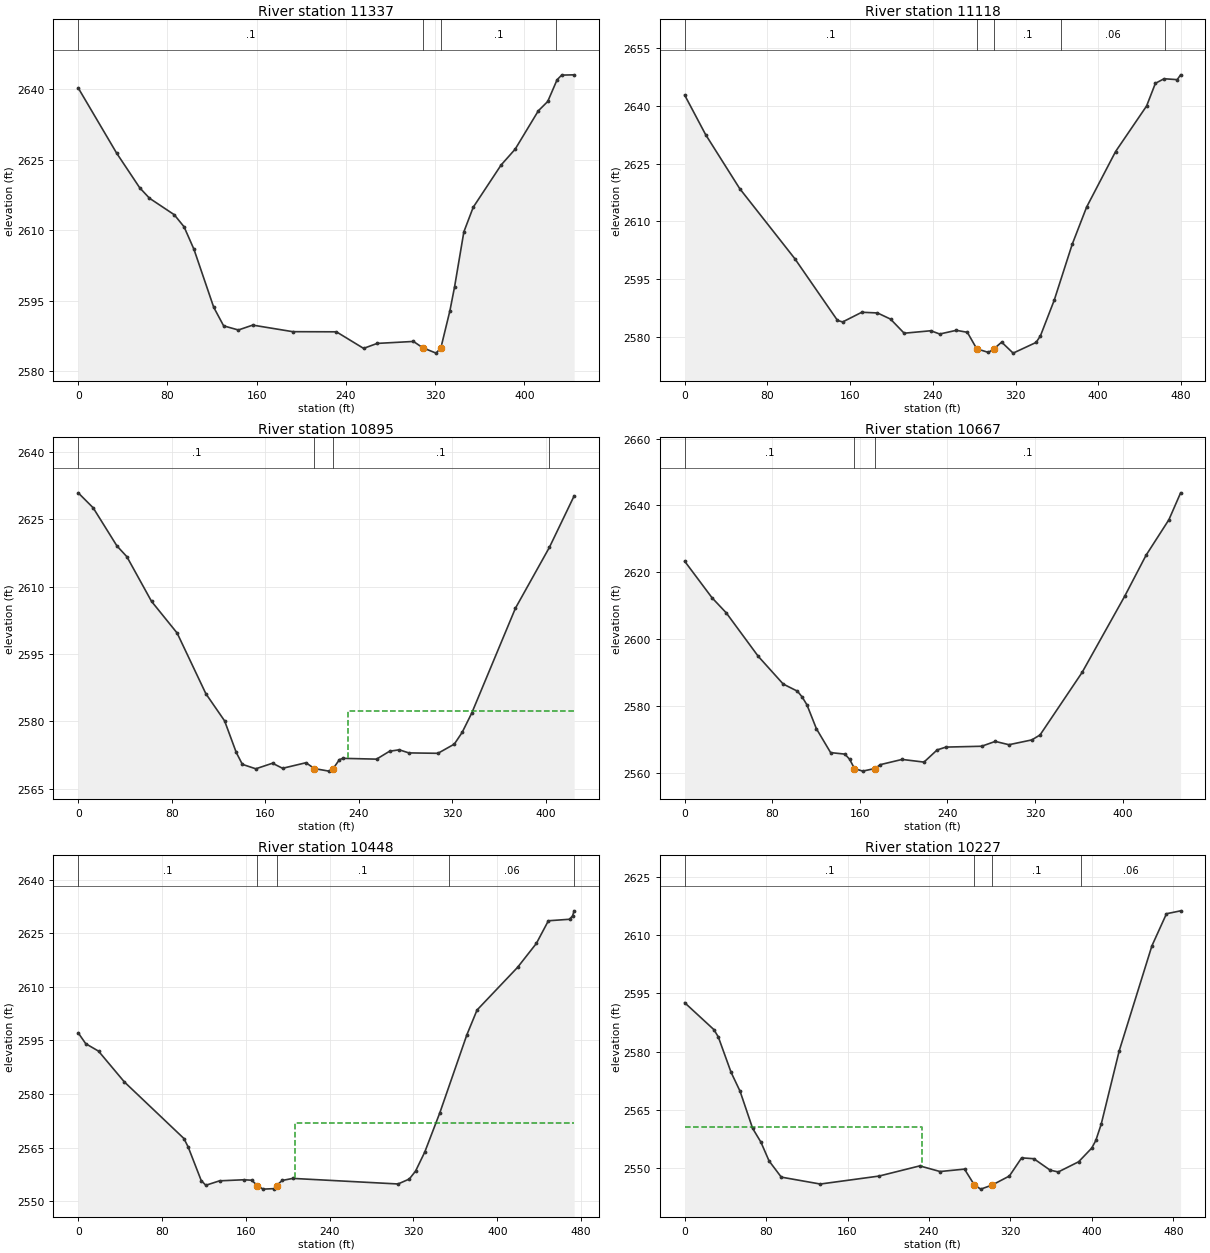
Type RM Length L Ch R = 1 ,11337   ,219.5,219.5,219.5
XS GIS Cut Line= 4
2252478.41868468569950.4441010472252680.94850824 570046.61845145
2252783.40263206 570064.979655072252894.82365205570098.541280771
#Sta/Elev= 30
       0 2640.32    34.4 2626.45    55.1 2619.06    63.9 2616.82    86.1 2613.31
    94.9 2610.74   103.8 2605.93   121.5 2593.59   130.4 2589.63   143.6 2588.75
   156.5 2589.79   192.4 2588.39   231.5 2588.36   255.9 2584.83   268.1 2585.89
   300.6 2586.31  308.89 2584.97   320.9 2583.82  325.242584.975   333.3 2592.86
   337.5 2597.97   345.8 2609.65   354.2  2614.9   379.2  2623.9   391.8 2627.27
   412.6 2635.45     421 2637.43   429.4 2642.06   433.5 2643.05   444.7 2643.11
#Mann= 4 ,-1,0
       0      .1       0  308.89    .045       0  325.24      .1       0
  428.29     .06       0
Bank Sta=308.89,325.24
XS Rating Curve= 0 ,0
Exp/Cntr=0.3,0.1

Type RM Length L Ch R = 1 ,11118   ,222.9,222.9,222.9
XS GIS Cut Line= 4
2252390.67584756 570124.471259942252623.24164271570216.085396611
2252691.48704313570281.4236947382252819.21384399570325.820666876
#Sta/Elev= 30
       0  2642.8    20.2 2632.55    53.2 2618.49   106.6 2600.23   147.8  2584.2
   152.8  2583.8   171.3 2586.32   186.5 2586.14   199.1 2584.54   212.3 2580.87
   238.1 2581.51   246.7 2580.66   262.7 2581.62   273.4 2581.11  282.492576.825
   293.8 2575.87  299.212576.828   306.6 2578.55   317.7 2575.69   339.9 2578.47
   344.1 2580.18   357.4 2589.42   374.8 2603.97   388.8 2613.69   416.8 2628.12
   446.8 2639.97   455.3 2645.86   463.7 2647.05   476.4 2646.82   479.7 2648.07
#Mann= 5 ,-1,0
       0      .1       0  282.49    .045       0  299.21      .1       0
  364.44     .06       0  464.44      .1       0
Bank Sta=282.49,299.21
XS Rating Curve= 0 ,0
Exp/Cntr=0.3,0.1

Type RM Length L Ch R = 1 ,10895   ,227.9,227.9,227.9
XS GIS Cut Line= 4
 2252341.0211526570336.000271959 2252469.2749461570382.418693536
2252563.17165652570451.2213219892252728.60316904 570495.88118008
#Sta/Elev= 30
       0  2630.9    12.8 2627.56    33.1 2619.08    41.6 2616.68    62.7 2606.73
    84.6 2599.67   109.2 2586.15   125.2 2580.11   135.2 2573.06   140.4 2570.42
   151.9 2569.43   166.2 2570.67   174.8 2569.54   194.8 2570.78     202 2569.48
   214.4 2568.91  218.072569.483   223.4 2571.46   226.3 2571.76   255.2 2571.58
   266.3 2573.34   274.6 2573.66   282.8 2572.97   307.7 2572.88   321.7 2574.93
   328.4 2577.54   336.6 2581.84     374 2605.21     403 2618.74   424.2 2630.22
#Mann= 4 ,-1,0
       0      .1       0     202    .045       0  218.07      .1       0
   402.8     .06       0
#XS Ineff= 2 , 0
                          230.35         2582.31
Permanent Ineff=
       F       F
Bank Sta=202,218.07
XS Rating Curve= 0 ,0
Exp/Cntr=0.3,0.1

Type RM Length L Ch R = 1 ,10667   ,218.5,218.5,218.5
XS GIS Cut Line= 4
2252265.10884305570528.3044424422252403.30190083570585.900387625
 2252513.0708429570581.8460083522252698.43859741570637.039190875
#Sta/Elev= 30
       0 2623.32      25 2612.38      38 2607.87    67.2 2594.87      90 2586.58
     103 2584.44   107.3 2582.71   111.7 2580.35   120.3 2573.23   133.3 2566.07
   146.3 2565.62   150.6 2564.11   155.1 2561.31   162.6 2560.53  173.792561.313
   178.6 2562.46   198.6 2564.03   218.6 2563.23   230.6 2566.87   238.6 2567.72
   271.2 2567.97   283.7 2569.42   296.2 2568.43   317.1 2569.87   324.6 2571.35
     363 2590.05   401.9 2612.84   421.4 2625.09   442.3 2635.74     453 2643.78
#Mann= 3 ,-1,0
       0      .1       0   155.1    .045       0  173.79      .1       0
Bank Sta=155.1,173.79
XS Rating Curve= 0 ,0
Exp/Cntr=0.3,0.1

Type RM Length L Ch R = 1 ,10448   ,221.6,221.6,221.6
XS GIS Cut Line= 4
 2252181.0867701570740.6182367512252293.72451559570762.338064622
2252485.28807788570846.7011851192252608.86218896 570930.61354476
#Sta/Elev= 30
       0  2597.1     7.2 2594.07    19.4 2591.99    44.1 2583.36   100.9 2567.55
     105 2565.15   117.4  2555.8   121.8 2554.47   134.9 2555.71   158.2 2556.01
   165.5 2555.88  171.122554.382   176.4 2553.39   187.3 2553.53  189.382554.381
   194.6 2555.81   204.8 2556.39   305.3 2554.83     316 2556.21     322 2558.42
   330.8 2563.76   345.2 2574.76     371 2596.57   380.7 2603.49   419.4 2615.43
   437.3 2622.11   448.8 2628.46     469 2628.88   471.9 2629.84   473.4 2631.24
#Mann= 5 ,-1,0
       0      .1       0  171.12    .045       0  189.38      .1       0
  354.03     .06       0   473.4      .1       0
#XS Ineff= 2 , 0
                           206.5          2571.9
Permanent Ineff=
       F       F
Bank Sta=171.12,189.38
XS Rating Curve= 0 ,0
Exp/Cntr=0.3,0.1

Type RM Length L Ch R = 1 ,10227   ,284.5,284.5,284.5
XS GIS Cut Line= 4
 2252032.9389285570979.5691856882252098.56014342571001.642872077
2252425.84044961571011.0356175312252504.71756779571055.513026688
#Sta/Elev= 30
       0 2592.63    28.7  2585.7      33 2583.84    45.6  2574.7    54.4 2569.84
    66.7 2560.31    74.9 2556.73    82.9  2551.9    94.9 2547.73   133.2 2545.95
   190.9    2548   230.9 2550.62   250.9 2549.17   274.9 2549.79  284.642545.689
   290.9 2544.64  302.05 2545.69     319 2548.02     331 2552.69     343 2552.47
     359 2549.53     367 2549.06     387 2551.68   399.9 2555.21   403.9 2557.17
   409.2 2561.37   426.9 2580.26     459 2607.27   473.3 2615.53   487.2 2616.28
#Mann= 4 ,-1,0
       0      .1       0  284.64    .045       0  302.05      .1       0
  389.23     .06       0
#XS Ineff= 2 , 0
          232.85 2560.55
Permanent Ineff=
       F       F
Bank Sta=284.64,302.05
XS Rating Curve= 0 ,0
Exp/Cntr=0.3,0.1

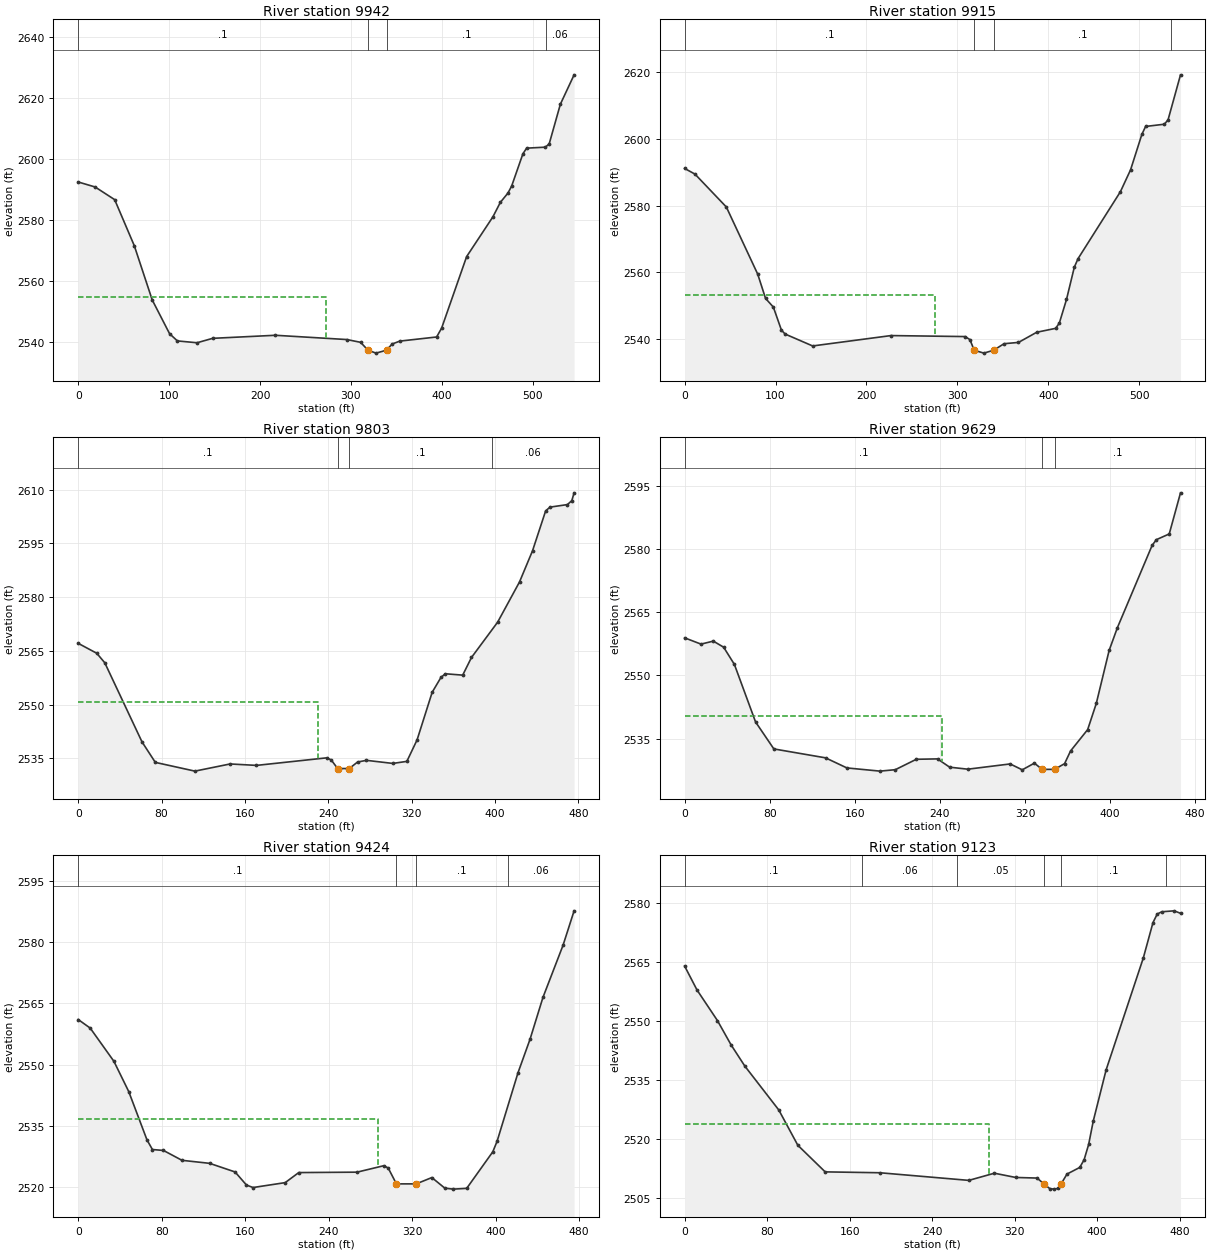
Type RM Length L Ch R = 1 ,9942    ,27.5,27.5,27.5
XS GIS Cut Line= 6
2251974.96490137571108.4305361392252225.32030312571209.372991686
2252218.59134261571233.7956558072252225.33711177571244.757530695
2252277.33574906571285.7942930952252442.76510722571327.588657593
#Sta/Elev= 30
       0 2592.59    18.6 2590.95    40.1  2586.8    61.7 2571.69    81.4 2553.93
   100.5 2542.86   109.1  2540.5   130.7  2539.9   147.9 2541.35   216.9 2542.35
   295.5 2540.95   310.6 2540.04   318.72537.471   327.5  2536.5  339.22 2537.47
   345.1 2539.46   353.7 2540.44   394.2 2541.79   399.7  2544.7   427.2 2568.14
   456.1 2581.17   464.3 2585.92   472.6 2588.94   476.7 2591.24   489.1 2601.83
   493.2 2603.68   513.8    2604     518 2605.08   530.3 2618.08   545.4 2627.71
#Mann= 4 ,-1,0
       0      .1       0   318.7    .045       0  339.22      .1       0
  514.77     .06       0
#XS Ineff= 2 , 0
          272.49 2554.97
Permanent Ineff=
       F       F
Bank Sta=318.7,339.22
XS Rating Curve= 0 ,0
Exp/Cntr=0.3,0.1

Type RM Length L Ch R = 1 ,9915    ,111.5,111.5,111.5
XS GIS Cut Line= 6
2251957.61505255571129.0790566172252207.97045429571230.021512163
2252201.24149378571254.4441762852252207.98726294571265.406051173
2252259.98590023571306.4428135732252425.41525839571348.237178071
#Sta/Elev= 30
       0 2591.15    11.4 2589.45    45.9 2579.59    80.4 2559.47      89 2552.21
    97.6  2549.6   106.5 2542.68   110.6 2541.52   140.8 2537.96     227 2541.07
   308.6 2540.77   313.8 2539.85  318.48 2536.68   329.1 2535.81  339.942536.682
   351.3 2538.63   367.2 2539.02   387.3 2542.07     408 2543.23   412.1 2544.79
     420 2551.88   428.6 2561.56   432.7 2564.12   479.3 2584.18   490.5 2590.76
   502.9 2601.36     507 2603.73   527.6  2604.4   531.7 2605.71   545.4  2619.2
#Mann= 4 ,-1,0
       0      .1       0  318.48    .045       0  339.94      .1       0
  534.77     .06       0
#XS Ineff= 2 , 0
          275.52  2553.1
Permanent Ineff=
       F       F
Bank Sta=318.48,339.94
XS Rating Curve= 0 ,0
Exp/Cntr=0.3,0.1

Type RM Length L Ch R = 1 ,9803    ,174.7,174.7,174.7
XS GIS Cut Line= 4
2251943.77699342571295.290792764 2252006.4466466571321.691106771
2252242.76947972571400.9756257962252394.24018137571448.011255877
#Sta/Elev= 30
       0  2567.1    17.8 2564.33    25.5 2561.68    61.2 2539.62      74 2533.89
     112 2531.45   145.8 2533.45   171.1 2533.05   238.6 2535.16   242.8 2534.57
     249 2532.17  260.122532.174   268.1 2533.99   276.6 2534.46   301.9  2533.6
   315.4 2534.17   325.2 2540.16   339.7 2553.45   348.1 2557.58   352.3 2558.61
     369 2558.23   377.4 2563.15   402.5    2573   423.5 2584.22     436 2592.92
   448.6 2604.06   452.8  2605.1   469.5 2605.81   473.7 2606.91   475.9 2609.09
#Mann= 4 ,-1,0
       0      .1       0     249    .045       0  260.12      .1       0
  397.27     .06       0
#XS Ineff= 2 , 0
          229.96 2550.69
Permanent Ineff=
       F       F
Bank Sta=249,260.12
XS Rating Curve= 0 ,0
Exp/Cntr=0.3,0.1

Type RM Length L Ch R = 1 ,9629    ,204.8,204.8,204.8
XS GIS Cut Line= 4
2251899.01829653571344.7798165712252050.88889197571461.100958906
2252158.94144225571547.038831257 2252294.6139712571565.351851327
#Sta/Elev= 30
       0 2558.95    15.4 2557.46      27 2558.17    36.7 2556.72    46.8 2552.63
    66.7 2538.95    83.9 2532.53   132.5 2530.41   152.6 2528.01   183.7 2527.25
   198.1 2527.59   217.9 2530.07   237.8 2530.16   249.2 2528.19   266.3 2527.71
   306.1 2528.96   317.5 2527.56   328.9 2529.15  336.152527.668  347.892527.669
   357.3 2529.03   362.9 2532.04     379 2537.13   387.1 2543.34   399.2 2555.97
     407  2561.4   439.6 2580.94   443.6  2582.3   455.7 2583.66   466.3 2593.44
#Mann= 3 ,-1,0
       0      .1       0  336.15    .045       0  347.89      .1       0
#XS Ineff= 2 , 0
          241.88 2540.41
Permanent Ineff=
       F       F
Bank Sta=336.15,347.89
XS Rating Curve= 0 ,0
Exp/Cntr=0.3,0.1

Type RM Length L Ch R = 1 ,9424    ,300.7,300.7,300.7
XS GIS Cut Line= 4
2251778.45098517571470.6572093862251982.44250919571647.772713492
2252108.68519446571685.4873825152252168.52345507571727.705876891
#Sta/Elev= 30
       0 2561.08    11.5 2558.98    34.2 2550.86    48.4 2543.46    65.9 2531.63
    71.1 2529.28    81.7 2529.05    99.4 2526.64   125.9  2525.9   150.3 2523.79
   161.2 2520.59   167.5 2519.98   198.3 2521.18   211.3 2523.64   267.1 2523.74
   292.8 2525.32     297 2524.75  304.872520.875  323.862520.875   338.8 2522.42
   351.3 2519.82   359.5 2519.59   372.2 2519.78   397.2 2528.72   401.3 2531.28
   421.4 2548.09   432.9 2556.27   445.3 2566.52   464.5 2579.24   475.1 2587.67
#Mann= 4 ,-1,0
       0      .1       0  304.87    .045       0  323.86      .1       0
  411.91     .06       0
#XS Ineff= 2 , 0
          287.45 2536.73
Permanent Ineff=
       F       F
Bank Sta=304.87,323.86
XS Rating Curve= 0 ,0
Exp/Cntr=0.3,0.1

Type RM Length L Ch R = 1 ,9123    ,281.3,281.3,281.3
XS GIS Cut Line= 5
2251583.52076949571791.9889486752251729.50094779571862.086787282
2251799.88434001571877.1277929542251947.83680524571916.486720902
2252032.55225131571956.993988296
#Sta/Elev= 30
       0 2563.97      12  2557.9    31.8 2550.14    45.1 2543.94    58.4 2538.57
    91.3 2527.44   109.8 2518.47   136.3 2511.72   189.2  2511.5   275.6 2509.56
   300.4 2511.38   321.1  2510.3   341.8 2510.15348.50432508.656   354.2 2507.45
   358.4 2507.34   362.5 2507.54365.05432508.645   370.8 2511.16   383.2 2512.85
   387.4 2514.79   391.8 2518.67   396.3 2524.64   408.8 2537.65   444.8    2566
   454.2    2575   458.3 2577.17   462.7 2577.75   474.8 2577.99   480.9 2577.36
#Mann= 6 ,-1,0
       0      .1       0  171.94     .06       0  263.91     .05       0
348.5043    .045       0365.0543      .1       0  467.01     .06       0
#XS Ineff= 2 , 0
          295.08 2523.92
Permanent Ineff=
       F       F
Bank Sta=348.5043,365.0543
XS Rating Curve= 0 ,0
Exp/Cntr=0.3,0.1

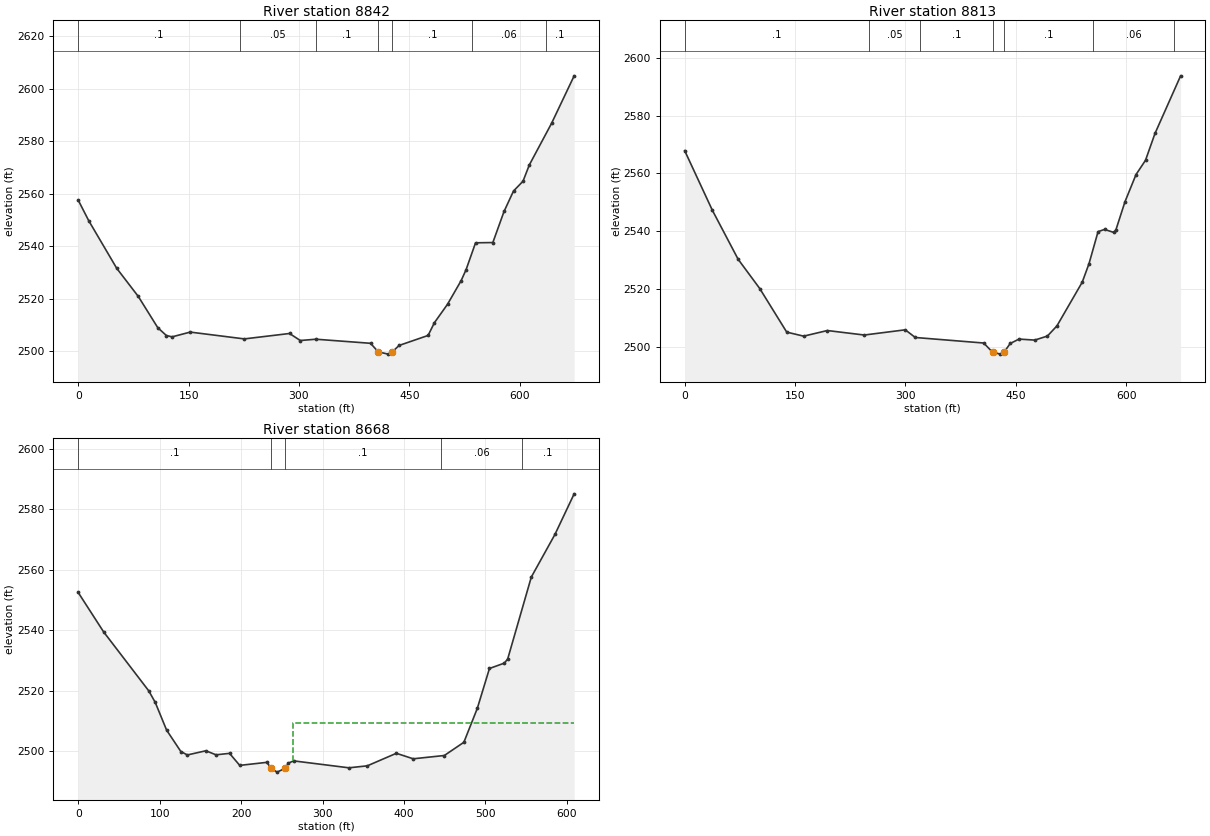
Type RM Length L Ch R = 1 ,8842    ,28.6,28.6,28.6
XS GIS Cut Line= 6
2251531.65505207571902.3802930962251812.47911714572061.206681295
2251774.84768231572104.134159336 2251768.7917276572172.186168436
2251772.16796457572198.9643877562251956.74235074572271.966960886
#Sta/Elev= 30
       0 2557.55    14.2 2549.78    52.3 2531.64    81.7  2520.9   108.1 2509.05
   119.8 2506.06   127.6 2505.55   152.2 2507.36   225.8 2504.77   287.2 2506.83
   301.8 2504.16     323 2504.65   397.3  2503.1  407.792499.832   421.4 2498.98
   426.9 2499.88   436.2 2502.29   475.5 2506.08   484.1 2510.94   501.9 2517.94
   520.4 2526.93   527.1 2531.08     540 2541.32   563.5 2541.42   578.7 2553.23
   591.6 2561.03   604.5 2564.74   613.1 2570.95   643.3 2586.76     674 2604.83
#Mann= 7 ,-1,0
       0      .1       0     220     .05       0  322.63      .1       0
  407.79    .045       0   426.9      .1       0  535.49     .06       0
  635.49      .1       0
Bank Sta=407.79,426.9
XS Rating Curve= 0 ,0
Exp/Cntr=0.3,0.1

Type RM Length L Ch R = 1 ,8813    ,145.4,145.4,145.4
XS GIS Cut Line= 6
2251507.40699271571905.3710828262251788.23105778572064.197471024
2251750.59962295572107.1249490662251744.54366824572175.176958166
2251747.91990522572201.9551774862251932.49429138572274.957750616
#Sta/Elev= 30
       0 2567.88    37.6 2547.31    72.7 2530.38     102 2520.31   138.7 2505.26
   161.7 2503.87   193.9 2505.81   244.1 2504.26   299.8 2506.06   313.4 2503.41
   406.4  2501.5   418.4 2498.33   429.2 2497.67  434.042498.327   442.4 2501.34
   454.4 2502.86   475.8 2502.51     493 2503.91   505.9 2507.41   540.3  2522.5
   549.5 2528.88   561.8 2539.93   570.6 2540.69   583.3 2539.65   586.1 2540.58
   598.4 2550.26   613.4 2559.63   626.3 2564.56   639.2 2573.83     674 2593.69
#Mann= 7 ,-1,0
       0      .1       0     250     .05       0     320      .1       0
   418.4    .045       0  434.04      .1       0  555.49     .06       0
  665.49      .1       0
Bank Sta=418.4,434.04
XS Rating Curve= 0 ,0
Exp/Cntr=0.3,0.1

Type RM Length L Ch R = 1 ,8668    ,208.4,208.4,208.4
XS GIS Cut Line= 5
2251441.21275596572059.0170066382251587.54323166572124.782956055
2251617.63058911572228.2725698962251641.84205933572311.649060782
2251886.88815003572377.918489307
#Sta/Elev= 30
       0 2552.49    31.1  2539.5    86.6 2519.96    94.6 2516.12   108.5 2506.98
     126 2499.89     134 2498.75   156.7 2500.13   169.2  2498.8   185.8 2499.28
   198.3  2495.3   231.7 2496.31  236.832494.295   244.2 2493.07  253.822494.296
   258.1 2496.06   264.5 2496.79   332.3  2494.5   354.9 2495.15   390.6  2499.3
   411.3 2497.48   449.5 2498.57   473.5 2502.94     490 2514.16   504.9 2527.35
   523.2 2529.13   527.3  2530.5   556.3  2557.6   585.3 2571.69   608.9 2585.13
#Mann= 5 ,-1,0
       0      .1       0  236.83    .045       0  253.82      .1       0
  445.03     .06       0  545.03      .1       0
#XS Ineff= 2 , 0
                          263.93          2509.4
Permanent Ineff=
       F       F
Bank Sta=236.83,253.82
XS Rating Curve= 0 ,0
Exp/Cntr=0.3,0.1