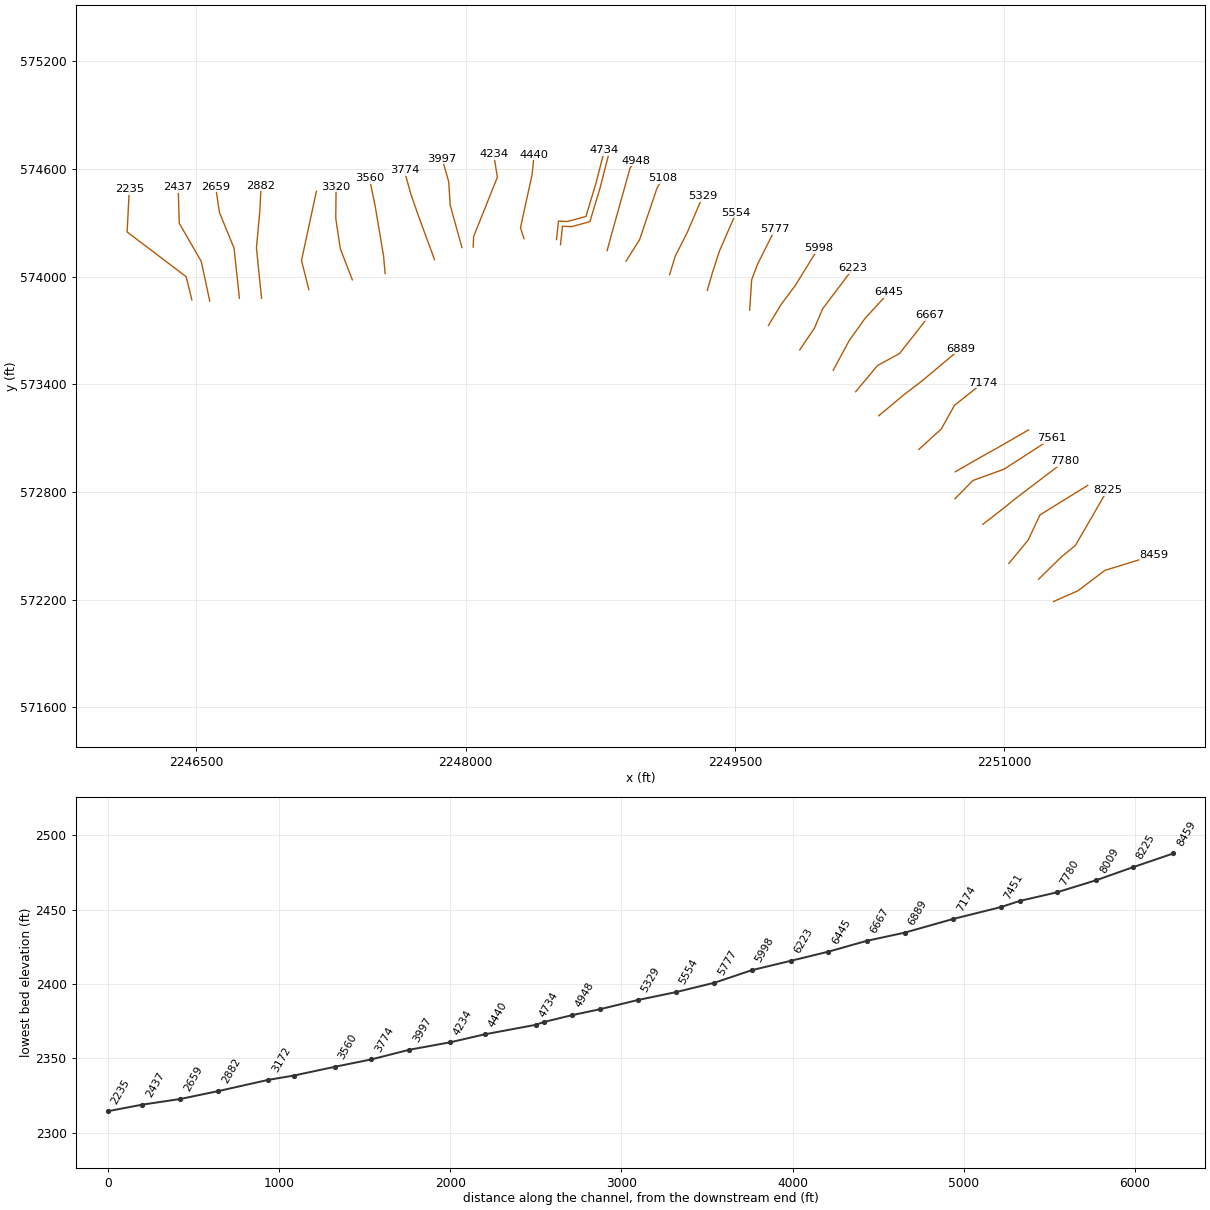
HEC-RAS study CONLEYRN.prj: CONLEYRN

--- CONLEYRN.g01 (geometry) --- (continued)

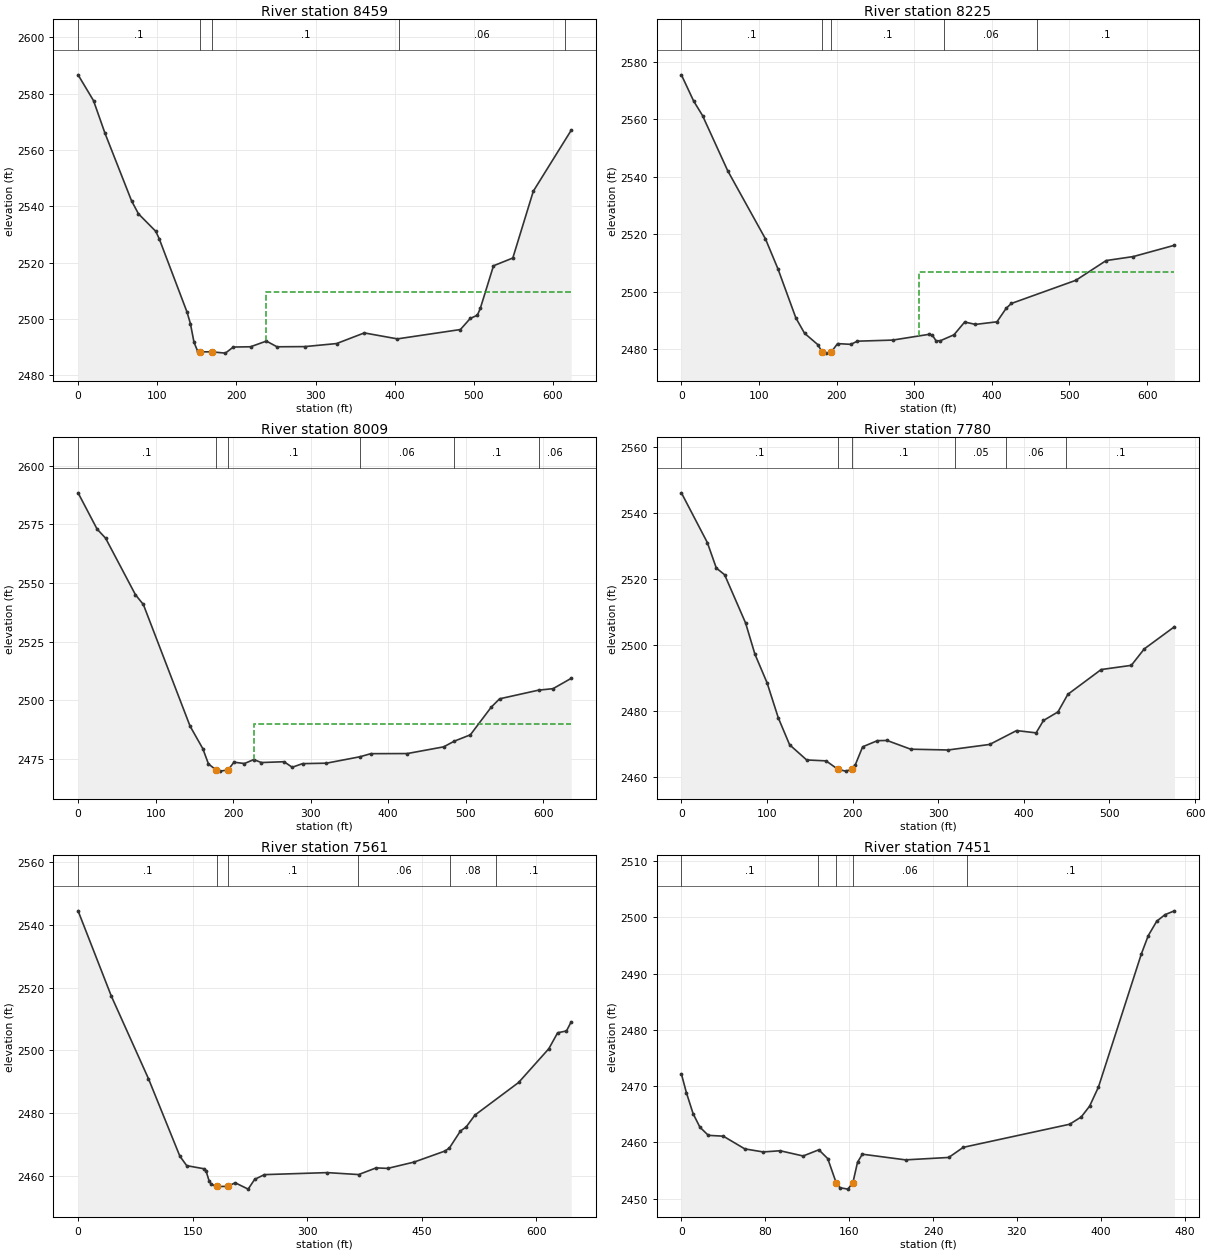
Type RM Length L Ch R = 1 ,8459    ,234.7,234.7,234.7
XS GIS Cut Line= 4
2251274.36621855 572189.95895056 2251410.2810485572250.040460744
2251559.36358754572362.9372660162251833.85143784572447.689429935
#Sta/Elev= 30
       0 2586.67    19.5 2577.51    34.1 2565.85    67.6  2541.9    76.3  2537.3
    98.2 2531.08   102.6 2528.39   137.6 2502.44   141.9 2498.33   146.5 2491.64
     151 2488.57   153.8 2488.28  168.692488.296   186.1 2487.83   196.1 2489.99
   217.9 2490.09   237.9 2492.11   251.3 2490.08   286.5 2490.15   326.6 2491.23
   361.6 2495.01   403.4 2492.89     483 2496.21   495.5 2500.17   504.4 2501.28
   508.1 2503.69   524.8 2518.85   549.2 2521.61   575.1 2545.34   622.9 2566.95
#Mann= 5 ,-1,0
       0      .1       0   153.8    .045       0  168.69      .1       0
  405.61     .06       0  615.61      .1       0
#XS Ineff= 2 , 0
                          237.03         2509.55
Permanent Ineff=
       F       F
Bank Sta=153.8,168.69
XS Rating Curve= 0 ,0
Exp/Cntr=0.3,0.1

Type RM Length L Ch R = 1 ,8225    ,215.9,215.9,215.9
XS GIS Cut Line= 4
2251190.80392048572314.1516766732251317.86837586572438.586238702
 2251395.6779835572502.0792485112251574.46428806572811.134166651
#Sta/Elev= 30
       0  2575.5    15.8 2566.37    27.2 2561.34    59.7  2542.1   108.3  2518.4
   124.4 2507.97   147.5 2490.87   158.7 2485.53   175.7 2481.59   181.3 2479.04
     186 2478.62  193.212479.043   201.2 2481.93   218.3 2481.68   226.8 2482.78
   272.3 2483.16   318.8 2485.15   323.4 2484.86   328.1 2482.91   333.6 2482.93
   351.2    2485     365 2489.45   378.9 2488.62   406.6 2489.52   418.5 2494.24
   425.1  2495.9   508.3 2503.98   547.3 2510.85   582.2 2512.23   635.3 2516.17
#Mann= 5 ,-1,0
       0      .1       0   181.3    .045       0  193.21      .1       0
  338.27     .06       0  458.27      .1       0
#XS Ineff= 2 , 0
                          306.79         2506.76
Permanent Ineff=
       F       F
Bank Sta=181.3,193.21
XS Rating Curve= 0 ,0
Exp/Cntr=0.3,0.1

Type RM Length L Ch R = 1 ,8009    ,229.1,229.1,229.1
XS GIS Cut Line= 5
2251025.03220387572401.7887987862251132.21307562 572531.48545722
2251169.44874082572610.4456116112251198.31299962572672.158232578
2251463.94492819572836.359538974
#Sta/Elev= 30
       0 2588.44    24.5    2573    35.5 2569.11      74 2545.02    84.2 2540.85
   144.5 2488.97   160.9  2479.4   168.2 2472.87  178.072470.334   183.4 2469.82
   193.5 2470.34   201.1 2473.63   214.6 2473.06   226.6 2474.75   236.5 2473.48
   265.7 2473.83   276.2 2471.47   289.5 2473.01   320.4 2473.21   363.7 2475.95
   377.6 2477.26   424.6 2477.31   471.6 2480.17   485.4 2482.61     506 2485.29
   532.8 2497.04   543.7 2500.64   593.9 2504.33   612.7 2504.97     636 2509.36
#Mann= 6 ,-1,0
       0      .1       0  178.07    .045       0   193.5      .1       0
   363.7     .06       0   485.4      .1       0   593.9     .06       0
#XS Ineff= 2 , 0
       0                   226.6       0    2490
Permanent Ineff=
       F       F
Bank Sta=178.07,193.5
XS Rating Curve= 0 ,0
Exp/Cntr=0.3,0.1

Type RM Length L Ch R = 1 ,7780    ,218.8,218.8,218.8
XS GIS Cut Line= 4
2250880.24721426572619.8427224422250989.14265931572704.231927463
2251068.29391911572767.9926551692251336.28573611572971.416855308
#Sta/Elev= 30
       0 2546.04    30.3 2530.97    40.8 2523.24    50.5 2521.21      75 2506.58
    85.9 2497.13   100.1 2488.44   113.2 2477.83   126.4 2469.68   146.3 2465.08
     169  2464.8   182.8 2462.24   191.8 2461.69   198.92462.237   203.2 2463.66
   211.7 2469.06     229 2470.93   240.2 2470.98   267.8 2468.34   311.5  2468.1
   360.1 2469.78   391.5 2473.98   414.3 2473.29   422.9 2477.04   439.8 2479.63
   451.4 2484.98   490.3 2492.48   525.5 2493.75   540.6 2498.73   575.9 2505.46
#Mann= 6 ,-1,0
       0      .1       0   182.8    .045       0   198.9      .1       0
  319.41     .05       0  379.41     .06       0  449.41      .1       0
Bank Sta=182.8,198.9
XS Rating Curve= 0 ,0
Exp/Cntr=0.3,0.1

Type RM Length L Ch R = 1 ,7561    ,110.4,110.4,110.4
XS GIS Cut Line= 4
2250724.86345117572762.078362452 2250824.5575757572863.646923951
2250998.20316959572926.8446094852251266.04869926 573099.79891003
#Sta/Elev= 30
       0 2544.47    43.6 2517.29    92.2 2491.02   133.3 2466.35   142.3 2463.31
   165.1 2462.31   167.5 2461.73   171.7 2458.42   174.4 2457.37   181.9 2456.69
  196.072456.694   205.8 2457.86   222.8 2455.83   231.3 2458.94   244.1 2460.45
   326.5 2461.09   367.5 2460.47   390.4 2462.59   405.6 2462.44   440.2 2464.45
   480.7 2467.97   486.5 2468.96   500.9 2474.35   508.4 2475.63   519.9 2479.42
   577.1  2489.8   616.7 2500.57   628.2 2505.63   639.8 2506.21   645.9  2509.1
#Mann= 6 ,-1,0
       0      .1       0   181.9    .045       0  196.07      .1       0
  367.11     .06       0  487.11     .08       0  547.11      .1       0
Bank Sta=181.9,196.07
XS Rating Curve= 0 ,0
Exp/Cntr=0.3,0.1

Type RM Length L Ch R = 1 ,7451    ,276.9,276.9,276.9
XS GIS Cut Line= 4
2250726.43683167572912.379035873   2250875.75755572998.068060432
2250964.14495788573047.0598355482251134.75145789573145.674396858
#Sta/Elev= 30
       0 2472.19     4.8 2468.84    11.2 2465.11    17.7 2462.71    25.7 2461.27
      40 2461.12    60.5 2458.86      78 2458.32    94.2 2458.53   116.1  2457.6
   131.1  2458.7   139.6 2457.13  147.61 2452.86   151.3 2451.96   158.8 2451.71
  163.592452.866     168 2456.49   172.6 2457.92   213.8 2456.91     255 2457.34
   268.9 2459.14   370.3 2463.24   381.4 2464.54   389.4 2466.47   397.8 2469.85
   438.7  2493.5   445.3 2496.76   453.4 2499.33   461.3 2500.49   470.3 2501.17
#Mann= 5 ,-1,0
       0      .1       0     130     .06       0  147.61    .045       0
  163.59     .06       0  272.16      .1       0
Bank Sta=147.61,163.59
XS Rating Curve= 0 ,0
Exp/Cntr=0.3,0.1

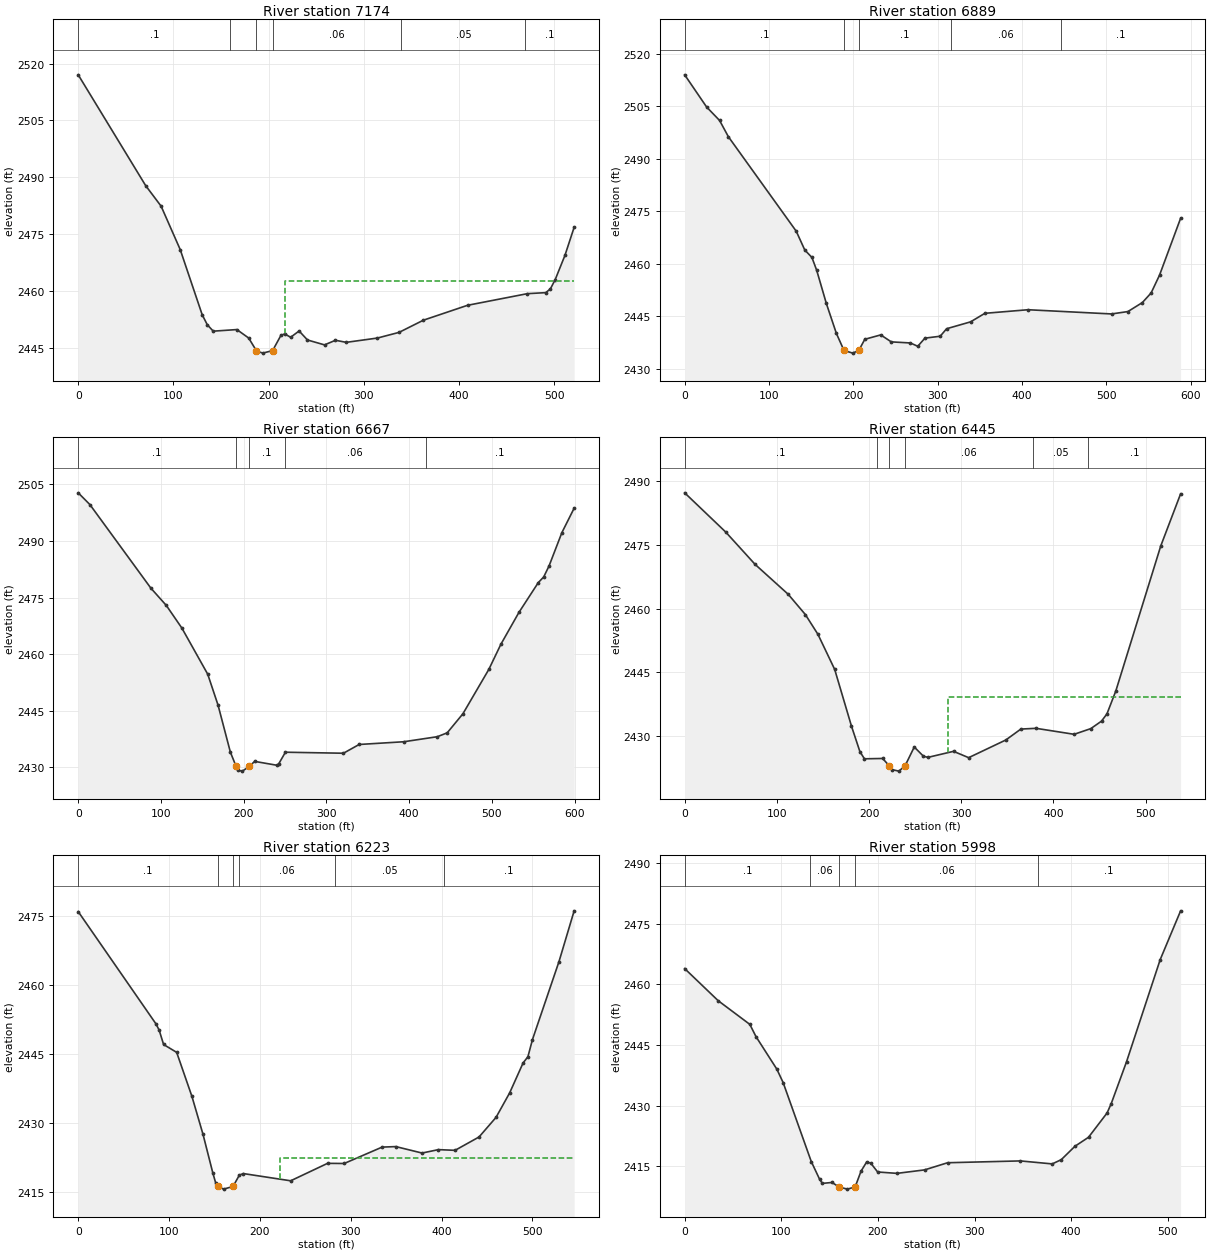
Type RM Length L Ch R = 1 ,7174    ,284.5,284.5,284.5
XS GIS Cut Line= 4
2250523.67403164 573037.168824532250648.72113412573150.640408199
2250722.17958227573282.3507960892250879.78333283573407.819748697
#Sta/Elev= 30
       0 2517.02    70.9 2487.85    87.1 2482.45   107.2 2471.01   130.3 2453.85
   135.7 2451.21   141.9 2449.55   166.7 2449.97   179.1 2447.75   187.2 2444.41
   193.8 2443.77  204.242444.428     213 2448.44     217 2448.83   223.2 2447.94
   232.1  2449.6   240.9 2447.23   258.8 2445.94   270.3 2447.15   281.7 2446.61
   314.4 2447.74   337.1 2449.23   362.7 2452.44   409.1 2456.36   471.9 2459.42
   491.2 2459.69   496.1 2460.66   501.2 2463.13   511.4 2469.48   521.1  2476.9
#Mann= 6 ,-1,0
       0      .1       0     160     .06       0   187.2    .045       0
  204.24     .06       0  339.67     .05       0  469.67      .1       0
#XS Ineff= 2 , 0
                          217.75         2462.71
Permanent Ineff=
       F       F
Bank Sta=187.2,204.24
XS Rating Curve= 0 ,0
Exp/Cntr=0.3,0.1

Type RM Length L Ch R = 1 ,6889    ,222.1,222.1,222.1
XS GIS Cut Line= 4
  2250300.419515573224.2923473372250438.43417632573339.758996492
2250538.31227883573416.1062034312250755.04819363573597.266708937
#Sta/Elev= 30
       0 2513.93      26 2504.75    41.4 2500.91    51.8 2496.28   132.3 2469.31
   142.4 2463.96   150.9 2461.82   156.6 2458.12     168 2448.69   179.9 2440.15
   188.9  2435.3   199.3 2434.53   206.52435.316   213.6 2438.48   232.5 2439.73
     245 2437.74   267.7 2437.43   276.4 2436.48   284.9 2438.81     303 2439.35
   310.6 2441.49     339 2443.45     356 2445.89   407.1 2446.91   506.2 2445.71
   525.6 2446.39   542.7 2448.95   553.1 2451.69   563.1 2456.78   588.1 2473.01
#Mann= 5 ,-1,0
       0      .1       0   188.9    .045       0   206.5      .1       0
  315.66     .06       0  445.66      .1       0
Bank Sta=188.9,206.5
XS Rating Curve= 0 ,0
Exp/Cntr=0.3,0.1

Type RM Length L Ch R = 1 ,6667    ,222.5,222.5,222.5
XS GIS Cut Line= 4
 2250171.9694769573358.3461137852250293.26550302573503.855077101
2250416.61432373573571.5165143462250582.94295227573783.203999137
#Sta/Elev= 30
       0 2502.73    14.1 2499.62    87.8 2477.48   106.5 2472.89   125.3 2466.89
   156.5 2454.69     169 2446.48   183.9 2434.02  190.782430.281   192.8 2429.23
   198.4 2429.01  206.842430.281   213.2 2431.59   239.7 2430.58   242.1 2430.87
   250.4 2434.02   320.5 2433.75   339.5 2436.07   393.3 2436.79     434 2438.13
   445.9 2439.16   464.9 2444.21   496.2 2455.96   510.7 2462.59   532.5 2471.03
     556 2478.96   562.5 2480.44     569 2483.38   584.5  2492.2   599.3 2498.67
#Mann= 5 ,-1,0
       0      .1       0  190.78    .045       0  206.84      .1       0
  249.43     .06       0  420.12      .1       0
Bank Sta=190.78,206.84
XS Rating Curve= 0 ,0
Exp/Cntr=0.3,0.1

Type RM Length L Ch R = 1 ,6445    ,221.4,221.4,221.4
XS GIS Cut Line= 4
2250046.87444064573477.9708843272250136.29085254573643.790061052
2250222.82123474573765.2343499262250358.10658346573913.004230963
#Sta/Elev= 30
       0 2487.28    44.5 2478.05    76.4 2470.43   112.3 2463.39   130.9 2458.62
   144.5 2453.98   162.7 2445.71   180.9 2432.36   190.1 2426.32     195 2424.66
   214.7 2424.74  222.052422.976   224.5 2422.13   232.3 2421.76  238.952422.974
     249 2427.44   258.9 2425.28   263.8    2425   291.6 2426.42     308 2424.93
   348.3 2429.09   364.6 2431.66     381 2431.84   422.4 2430.43   440.5 2431.77
   452.1 2433.53     458 2435.24   467.6 2440.62   516.4  2474.8   537.9 2487.05
#Mann= 6 ,-1,0
       0      .1       0  208.39     .06       0  222.05    .045       0
  238.95     .06       0  377.51     .05       0  437.51      .1       0
#XS Ineff= 2 , 0
                          285.92         2439.19
Permanent Ineff=
       F       F
Bank Sta=222.05,238.95
XS Rating Curve= 0 ,0
Exp/Cntr=0.3,0.1

Type RM Length L Ch R = 1 ,6223    ,225.3,225.3,225.3
XS GIS Cut Line= 4
2249860.29516854573591.2913444882249942.49860925 573713.09505911
2249987.63226824573820.056578613  2250158.246988574045.761950178
#Sta/Elev= 30
       0 2475.85    85.6 2451.46    89.1 2450.11      94 2446.98   108.4 2445.27
   125.2  2435.7   137.4 2427.46   148.3    2419   151.3 2416.95  153.762416.133
   160.1 2415.56  170.462416.141   177.4  2418.6   181.8 2418.94   233.9 2417.37
   274.5 2421.16   292.8 2421.13   334.6 2424.69   349.7  2424.8   378.5  2423.4
   396.6 2424.14   414.9 2423.99   441.3 2426.89     460 2431.15     475 2436.47
   489.8 2442.98   495.1 2444.32   500.1 2448.05   529.3 2464.99     546 2476.02
#Mann= 6 ,-1,0
       0      .1       0  153.76    .045       0  170.46      .1       0
  176.95     .06       0  283.04     .05       0  403.04      .1       0
#XS Ineff= 2 , 0
                          221.85         2422.41
Permanent Ineff=
       F       F
Bank Sta=153.76,170.46
XS Rating Curve= 0 ,0
Exp/Cntr=0.3,0.1

Type RM Length L Ch R = 1 ,5998    ,220.5,220.5,220.5
XS GIS Cut Line= 4
2249686.00625439573727.4947747012249757.46471655573845.708218192
 2249833.9315775573947.5308822242249964.21562862574158.210871112
#Sta/Elev= 30
       0 2463.89    34.7 2455.94    67.4 2450.09    73.8 2447.06    95.4    2439
   101.9 2435.68     131 2416.15   139.7 2411.73   142.5 2410.75   152.5 2410.98
   159.7 2409.86   168.3 2409.33   176.4 2409.86   182.5 2413.78   188.3 2416.04
   192.5 2415.77   199.7 2413.57   219.7 2413.23   248.3 2414.09   272.1 2415.86
   347.4 2416.31   380.3 2415.57   389.7 2416.62   403.8 2419.92   417.9 2422.16
   437.1 2428.17   441.4 2430.49   457.2 2440.82   492.1 2466.13   513.2 2478.18
#Mann= 5 ,-1,0
       0      .1       0     130     .06       0   159.7    .045       0
   176.4     .06       0  365.47      .1       0
Bank Sta=159.7,176.4
XS Rating Curve= 0 ,0
Exp/Cntr=0.3,0.1

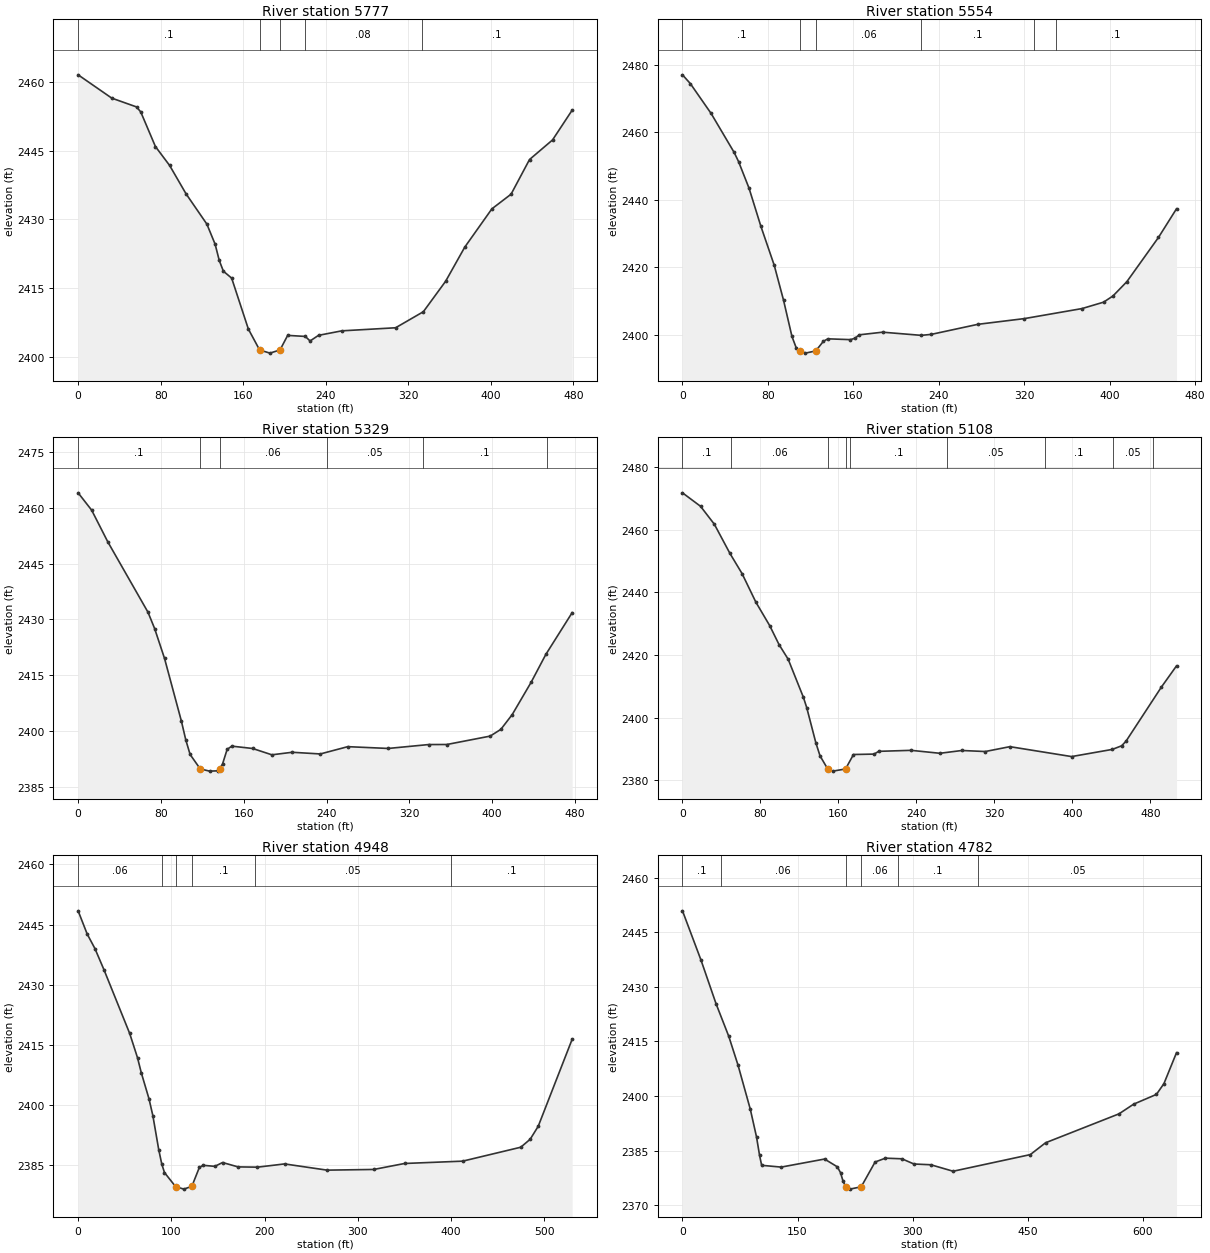
Type RM Length L Ch R = 1 ,5777    ,223.4,223.4,223.4
XS GIS Cut Line= 4
2249581.48382344  573812.65374182249592.65448937573982.209273391
2249625.68025204574069.0560728892249722.45094755574262.124564939
#Sta/Elev= 30
       0 2461.51    32.6 2456.43    56.6 2454.51    60.7 2453.42    74.9 2445.88
    88.7 2441.74   104.6 2435.56   124.8 2428.95   132.8 2424.56   136.8 2421.02
   140.8 2418.68   148.8 2417.18     165 2406.07   175.9 2401.51   185.9 2400.82
  195.682401.517   203.1 2404.69   220.2 2404.46   224.8 2403.47     233  2404.7
   255.6 2405.68   307.7 2406.35   334.6 2409.85   356.2  2416.5   374.8 2423.96
     401 2432.28   419.6 2435.48   437.5 2443.04   459.8 2447.31   478.8  2453.8
#Mann= 5 ,-1,0
       0      .1       0   175.9    .045       0  195.68      .1       0
  219.92     .08       0  332.84      .1       0
Bank Sta=175.9,195.68
XS Rating Curve= 0 ,0
Exp/Cntr=0.3,0.1

Type RM Length L Ch R = 1 ,5554    ,224.6,224.6,224.6
XS GIS Cut Line= 4
 2249345.4494002573922.7326785912249374.33276624574022.197163583
 2249413.1367601574141.8811989722249506.00022006 574355.78102138
#Sta/Elev= 30
       0 2477.06     7.4 2474.44    26.8 2465.61    48.4 2454.04    52.5 2451.35
    62.3 2443.47    73.4 2432.16    85.9 2420.61    94.6 2410.27   102.5  2399.5
   106.7 2395.94  110.152395.199   115.1 2394.55   124.82395.204   131.9 2398.04
   136.1 2398.79   157.2 2398.55   161.4 2398.94   165.6 2399.98   187.4 2400.76
   223.6 2399.82     233 2400.11   276.6 2403.09   320.2 2404.79   374.1 2407.76
   394.3 2409.66   403.1  2411.5   416.1 2415.73   445.7 2428.85   462.6 2437.35
#Mann= 6 ,-1,0
       0      .1       0  110.15    .045       0   124.8     .06       0
  223.57      .1       0  329.39     .05       0  349.39      .1       0
Bank Sta=110.15,124.8
XS Rating Curve= 0 ,0
Exp/Cntr=0.3,0.1

Type RM Length L Ch R = 1 ,5329    ,221.6,221.6,221.6
XS GIS Cut Line= 4
2249135.18082654574009.8010635762249167.69740139574115.044066995
2249232.49598049574242.1898669622249320.90540942574448.452196363
#Sta/Elev= 30
       0 2464.04    13.1 2459.37    28.7 2450.84    67.5 2431.93    73.9 2427.55
    83.5 2419.49    99.8 2402.62     104 2397.61   108.2 2393.67     118 2389.78
     127 2389.19     135 2389.27  136.79 2389.79   139.5 2391.08     144 2395.06
   148.5 2395.91   168.6 2395.28   187.2 2393.58   206.8 2394.26     234 2393.81
   260.5 2395.77   299.6 2395.29   338.8 2396.34   356.2 2396.35   398.1 2398.61
   408.4 2400.42   419.4  2404.4   437.7  2413.1   451.9 2420.59   477.3 2431.81
#Mann= 6 ,-1,0
       0      .1       0     118    .045       0  136.79     .06       0
  240.15     .05       0  332.86      .1       0  452.86     .05       0
Bank Sta=118,136.79
XS Rating Curve= 0 ,0
Exp/Cntr=0.3,0.1

Type RM Length L Ch R = 1 ,5108    ,159.7,159.7,159.7
XS GIS Cut Line= 4
2248892.73822739 574085.531025572248968.49282072574205.325440984
2249064.82515817574490.7003098792249095.88392663574546.405409449
#Sta/Elev= 30
       0 2471.72    18.5 2467.43    32.7  2461.7    48.6 2452.44    61.1 2445.97
    75.3 2436.84    89.5 2429.35      99 2423.35   108.4 2418.66     124 2406.53
   127.4 2403.26   136.8    2392   141.1 2387.83  148.982383.655   154.2 2382.98
  167.222383.668   175.4 2388.28   196.5 2388.41   201.3 2389.29   234.5 2389.61
     264 2388.67   286.6 2389.56   310.5 2389.23   335.8 2390.78   399.1 2387.62
   440.9 2389.91   450.4 2391.06   454.9 2392.52   491.3 2409.83   506.7 2416.54
#Mann= 9 ,-1,0
       0      .1       0      50     .06       0  148.98    .045       0
  167.22     .06       0  171.74      .1       0  271.74     .05       0
  371.74      .1       0  441.74     .05       0  482.93      .1       0
Bank Sta=148.98,167.22
XS Rating Curve= 0 ,0
Exp/Cntr=0.3,0.1

Type RM Length L Ch R = 1 ,4948    ,166.3,166.3,166.3
XS GIS Cut Line= 4
2248787.59462951 574143.764345972248808.25108876574220.770101816
2248915.40599838574604.245801069 2248947.4191069574645.167931145
#Sta/Elev= 30
       0 2448.44     9.7 2442.67      18 2439.05    27.8 2433.72    55.3 2417.89
    63.7 2411.83    67.7 2408.13      76 2401.61    80.2 2397.36    86.5 2388.86
    89.7 2385.37    92.6 2383.23  104.562379.722   113.4  2379.1  121.982379.804
     130 2384.49   134.1 2385.04   146.6 2384.77   154.9 2385.73   171.5 2384.64
   192.3 2384.57   221.4 2385.38     267 2383.83     317    2384   350.1 2385.49
   412.4 2386.07   474.7 2389.54   484.8 2391.53   493.4 2394.75   529.8 2416.44
#Mann= 6 ,-1,0
       0     .06       0   89.73      .1       0  104.56    .045       0
  121.98      .1       0  189.73     .05       0  399.73      .1       0
Bank Sta=104.56,121.98
XS Rating Curve= 0 ,0
Exp/Cntr=0.3,0.1

Type RM Length L Ch R = 1 ,4782    ,48,48,48
XS GIS Cut Line= 6
  2248527.900497574177.2594453672248538.81945233574279.857881663
2248589.12858389574277.451366207 2248691.6963969574305.552063465
2248748.10403728574492.4054055452248794.77993039574674.534145121
#Sta/Elev= 30
       0 2450.85    24.1 2437.34    43.8 2425.31    60.3 2416.41    72.3 2408.55
    88.4 2396.38    96.5 2388.77   100.5 2383.68   103.2 2380.97   128.7 2380.48
   185.2 2382.69   201.8 2380.56   206.1 2378.92   209.3  2376.6  212.842375.083
   218.1 2374.43  232.962375.063   251.1 2381.88   264.5 2382.93     286 2382.76
   301.7 2381.33   323.8 2381.12   352.8 2379.34   453.4 2383.91   473.3 2387.16
     569  2395.1   588.1 2397.76   617.8 2400.44   627.6  2403.4     644  2411.9
#Mann= 6 ,-1,0
       0      .1       0      50     .06       0  212.84    .045       0
  232.96     .06       0   280.7      .1       0  385.73     .05       0
Bank Sta=212.84,232.96
XS Rating Curve= 0 ,0
Exp/Cntr=0.3,0.1

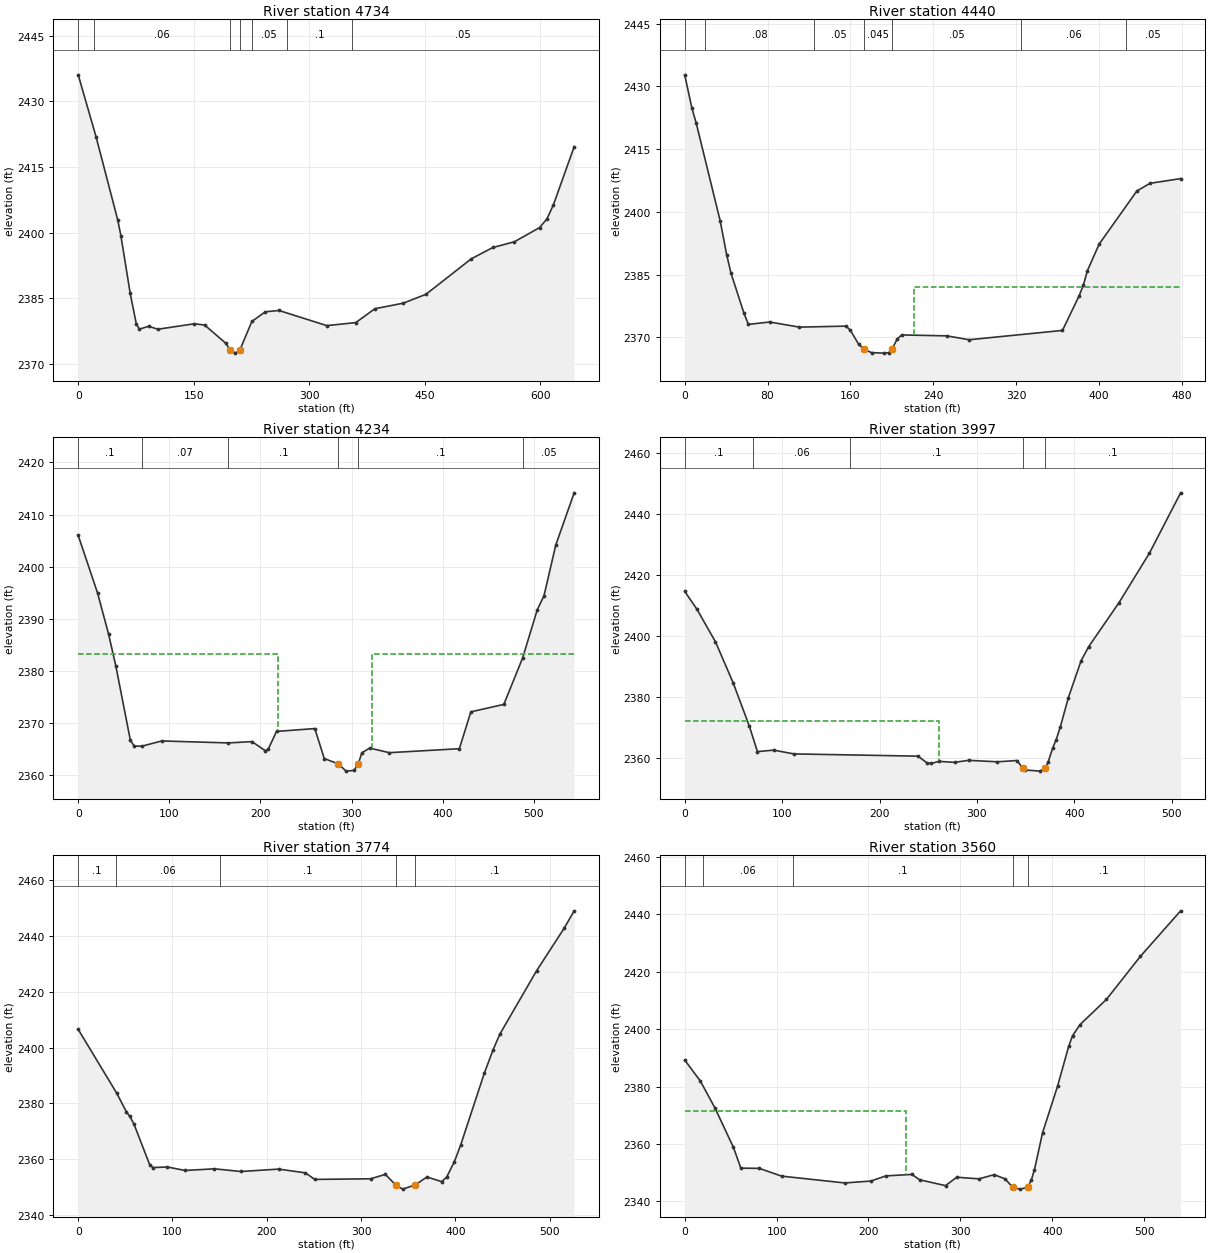
Type RM Length L Ch R = 1 ,4734    ,294.1,294.1,294.1
XS GIS Cut Line= 6
2248505.67280024574206.0786837212248516.59175557574308.677120016
2248566.90088713574306.2706045612248669.46870014574334.371301818
2248725.87634052574521.2246438992248772.55223363574703.353383475
#Sta/Elev= 30
       0 2436.04    23.2 2421.88    51.4 2402.86    55.4 2399.36    67.5 2386.19
    75.5 2379.13    79.5 2378.01    91.6 2378.66   103.2 2377.98   150.9 2379.23
   164.2 2378.94   191.6 2374.79   197.4  2373.2   204.2 2372.53  209.832373.197
   225.5 2379.76   243.1 2381.97   260.7 2382.26   322.8 2378.81   360.5  2379.5
   385.2 2382.66   422.1 2383.93   451.7 2385.97   510.4 2394.05   538.5 2396.64
   566.3 2397.93   599.1 2401.18   608.7 2403.18   616.9 2406.29     644 2419.62
#Mann= 7 ,-1,0
       0      .1       0      20     .06       0   197.4    .045       0
  209.83     .06       0  225.48     .05       0   270.7      .1       0
  355.73     .05       0
Bank Sta=197.4,209.83
XS Rating Curve= 0 ,0
Exp/Cntr=0.3,0.1

Type RM Length L Ch R = 1 ,4440    ,205.8,205.8,205.8
XS GIS Cut Line= 4
2248324.51187018574210.5401638742248304.99278137574272.540114082
2248369.39820203 574566.375254682248381.09590299574678.569814463
#Sta/Elev= 30
       0 2432.78       7  2424.8    11.2 2421.16    34.3 2397.81    40.5 2389.79
    44.7 2385.33    57.3  2375.7    61.5 2373.09      82 2373.66   110.7 2372.44
   155.7 2372.68   159.8 2371.71     168 2368.31  172.78 2367.17   180.3 2366.34
   192.5 2366.22   196.7  2366.3  200.122367.172   204.9 2369.52   209.3 2370.57
   252.9 2370.35   274.5 2369.42   364.6 2371.65   380.7 2379.96   384.7 2382.44
   388.7 2385.97     400  2392.3   436.4 2405.01   449.1 2406.83   478.6 2407.96
#Mann= 7 ,-1,0
       0      .1       0      20     .08       0     125     .05       0
  172.78    .045       0  200.12     .05       0     325     .06       0
  425.81     .05       0
#XS Ineff= 2 , 0
                          221.66         2382.07
Permanent Ineff=
       F       F
Bank Sta=172.78,200.12
XS Rating Curve= 0 ,0
Exp/Cntr=0.3,0.1

Type RM Length L Ch R = 1 ,4234    ,236.9,236.9,236.9
XS GIS Cut Line= 4
2248041.41947485574163.9510079342248043.88966055574222.087000378
2248176.30677164574553.2935721052248155.58700489574681.116567478
#Sta/Elev= 30
       0 2405.99    21.2 2394.96    33.3 2387.08    41.3 2380.95    57.3 2366.66
    61.5 2365.59      70 2365.57    91.7 2366.57   164.9 2366.19   190.8 2366.44
   205.4 2364.69   208.5 2364.96   217.7  2368.4   259.7 2368.94   270.1 2363.19
  285.492362.181   294.1 2360.78   302.8 2360.92   307.42362.184   311.4 2364.31
     320  2365.2   341.5 2364.32   418.4 2365.08     431 2372.15   467.2 2373.58
   487.7 2382.42   503.9 2391.72   511.3 2394.42   524.2 2404.13   544.4 2414.16
#Mann= 6 ,-1,0
       0      .1       0      70     .07       0   164.9      .1       0
  285.49    .045       0   307.4      .1       0   487.7     .05       0
#XS Ineff= 2 , 0
       0  218.77 2383.17   322.4       0 2383.17
Permanent Ineff=
       F       F
Bank Sta=285.49,307.4
XS Rating Curve= 0 ,0
Exp/Cntr=0.3,0.1

Type RM Length L Ch R = 1 ,3997    ,222.7,222.7,222.7
XS GIS Cut Line= 4
2247978.99140722574161.1572391162247913.49469008574397.235127724
 2247905.2329534574527.5138488522247868.75996192574656.049484977
#Sta/Elev= 30
       0 2414.77    12.5 2408.94    31.6 2398.22    49.8 2384.74    66.4 2370.54
    74.7  2362.2    91.3 2362.69   112.1 2361.45   239.5 2360.71   248.9 2358.48
     253 2358.32     261    2359     277 2358.68   291.4 2359.34   321.1 2358.86
   341.1 2359.28  347.022356.845   349.1 2356.17   365.2  2355.8  370.162356.844
   373.2 2358.85   377.7 2363.31   381.4 2366.17   385.6 2370.27   393.8 2379.83
   406.9 2391.98   414.7 2396.61   445.8 2411.04   477.1  2427.3   509.1 2447.08
#Mann= 5 ,-1,0
       0      .1       0      70     .06       0     170      .1       0
  347.02    .045       0  370.16      .1       0
#XS Ineff= 2 , 0
          261.32 2372.13
Permanent Ineff=
       F       F
Bank Sta=347.02,370.16
XS Rating Curve= 0 ,0
Exp/Cntr=0.3,0.1

Type RM Length L Ch R = 1 ,3774    ,214.1,214.1,214.1
XS GIS Cut Line= 4
2247826.32140703574093.7251626242247739.61754876574328.906159189
2247693.65549759  574461.36252242247657.69374632574591.735584657
#Sta/Elev= 30
       0 2406.55    40.9 2383.66    51.1    2377    54.8 2375.33    59.1 2372.63
      76 2357.91    79.1 2357.03    94.7 2357.22   113.4 2355.98   144.5 2356.57
   172.6 2355.61   212.6 2356.47   241.1 2355.12   250.9 2352.77   310.2    2353
   325.9 2354.58   336.72350.777   344.1 2349.29  357.522350.777   369.9 2353.65
   385.6 2351.98   390.9 2353.63     399 2359.11   405.7 2365.08   430.9 2390.95
     440 2399.13   447.2  2404.8   486.2 2427.55   515.5 2442.82   526.1 2449.06
#Mann= 5 ,-1,0
       0      .1       0      40     .06       0     150      .1       0
   336.7    .045       0  357.52      .1       0
Bank Sta=336.7,357.52
XS Rating Curve= 0 ,0
Exp/Cntr=0.3,0.1

Type RM Length L Ch R = 1 ,3560    ,239.7,239.7,239.7
XS GIS Cut Line= 4
2247551.05840481574016.2825817292247542.40115989 574113.89536453
2247496.11602497574389.6799009132247463.46370352574548.347308396
#Sta/Elev= 30
       0 2389.26      17 2381.97      33 2372.53    53.1  2358.8    61.1 2351.61
    81.2 2351.53   105.4 2348.83   174.3 2346.45   202.7 2347.12   218.9 2348.91
   247.3 2349.42   255.6 2347.56   283.8 2345.52     296 2348.44   320.3 2347.88
   336.6 2349.33   348.7 2347.87   356.8 2344.96     365  2344.3   373.1 2344.93
   377.2 2347.52   380.6  2351.1   389.4 2363.95   405.7 2380.13   417.8    2394
     422  2397.7   430.2 2401.61   458.8 2410.34   495.7 2425.31   539.6 2441.21
#Mann= 5 ,-1,0
       0      .1       0      20     .06       0     118      .1       0
   356.8    .045       0   373.1      .1       0
#XS Ineff= 2 , 0
          240.87 2371.45
Permanent Ineff=
       F       F
Bank Sta=356.8,373.1
XS Rating Curve= 0 ,0
Exp/Cntr=0.3,0.1

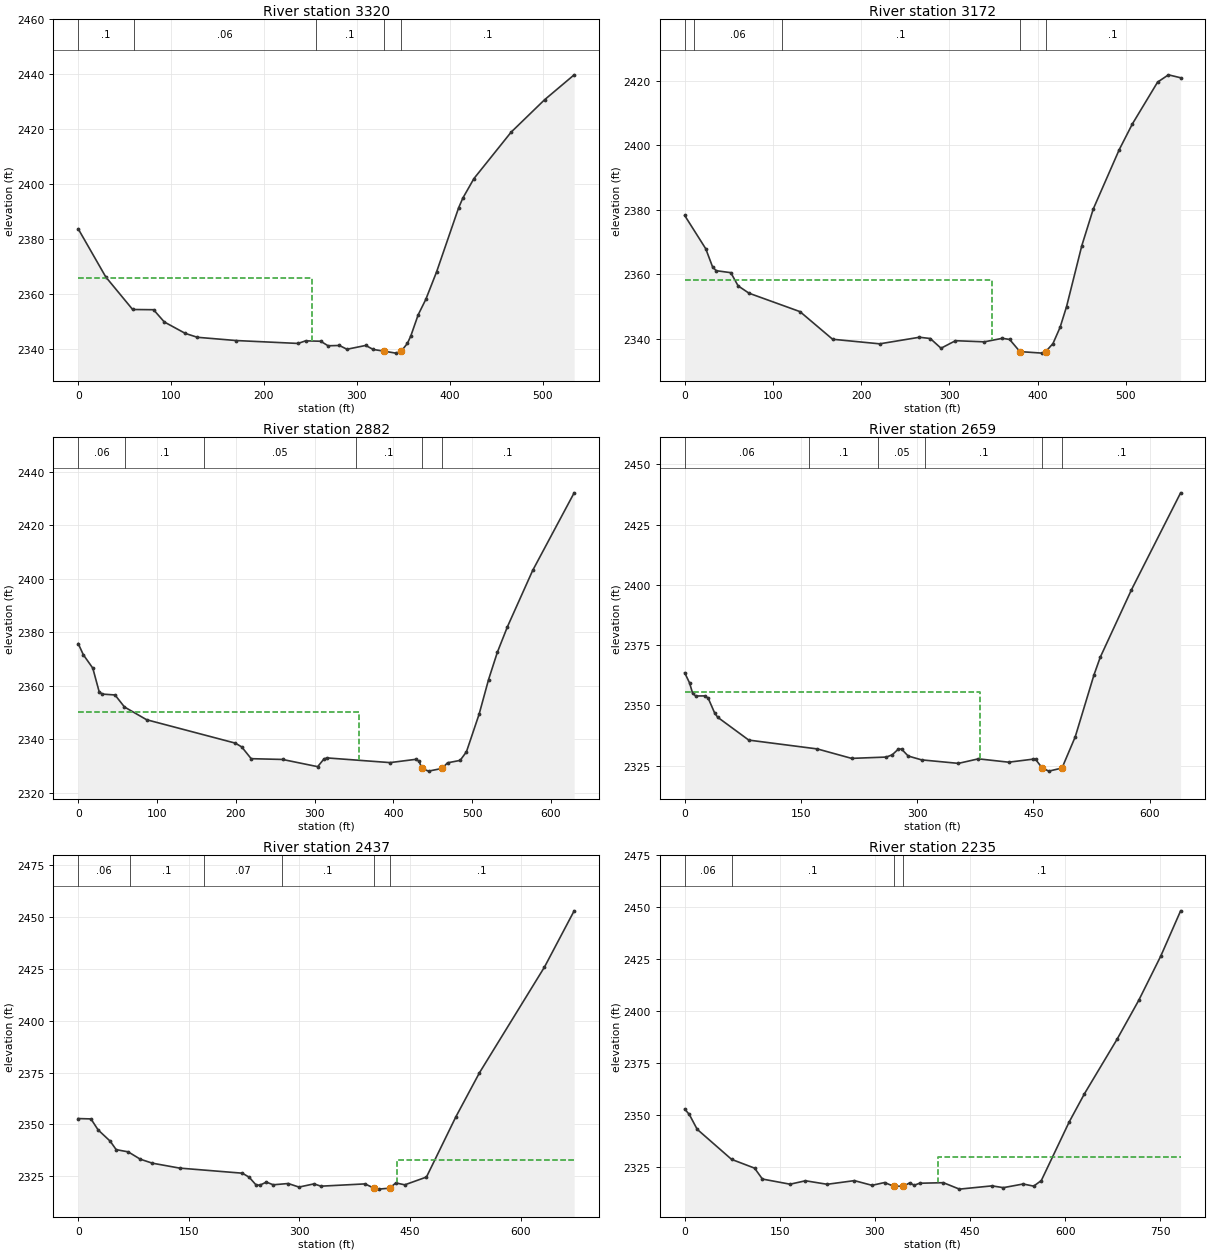
Type RM Length L Ch R = 1 ,3320    ,148,148,148
XS GIS Cut Line= 4
2247368.26461026573981.4735597142247301.53660085574154.670539316
2247276.13385042574323.550199321 2247277.9265049574501.024794412
#Sta/Elev= 30
       0 2383.69    29.7 2366.15    58.6  2354.3    81.1 2354.22    92.7 2349.75
   115.4 2345.57   128.3 2344.17     170 2342.99   236.7 2341.93   244.8 2342.88
     261 2342.73     269 2341.08   281.2 2341.19   289.3 2339.81   309.5  2341.2
   317.6 2339.73   329.7 2339.09   341.9  2338.4   347.72339.097   354.3 2341.91
     358 2344.61     366 2352.38   374.2 2357.99   385.8    2368   409.5 2391.33
     414 2394.86     426 2402.01     466 2418.91     502 2430.72   533.9 2439.82
#Mann= 5 ,-1,0
       0      .1       0      60     .06       0  255.61      .1       0
   329.7    .045       0   347.7      .1       0
#XS Ineff= 2 , 0
          252.13 2365.93
Permanent Ineff=
       F       F
Bank Sta=329.7,347.7
XS Rating Curve= 0 ,0
Exp/Cntr=0.3,0.1

Type RM Length L Ch R = 1 ,3172    ,290.7,290.7,290.7
XS GIS Cut Line= 4
2247126.44098121573926.4401799582247085.25184879 574089.03064407
2247137.97077707574334.0227896222247168.29937281574474.619268176
#Sta/Elev= 30
       0  2378.2    23.9 2367.87    31.7  2362.2    35.8 2361.08    52.3 2360.47
    60.6 2356.37      73  2354.1   130.7  2348.4   167.7 2339.84   221.1 2338.42
   266.1 2340.46   278.4 2340.07   290.6 2337.06     307 2339.39   339.7 2339.04
   360.2 2340.13   368.4 2339.77  379.982336.016   405.2 2335.54   409.3 2336.02
   417.5  2338.5   425.6 2343.56   432.9 2349.96   450.2 2368.85   463.2 2380.22
   492.6 2398.58   507.5 2406.55   536.1 2419.51   548.4 2421.77   562.2 2420.86
#Mann= 5 ,-1,0
       0      .1       0      10     .06       0     110      .1       0
  379.98    .045       0   409.3      .1       0
#XS Ineff= 2 , 0
          347.87 2358.28
Permanent Ineff=
       F       F
Bank Sta=379.98,409.3
XS Rating Curve= 0 ,0
Exp/Cntr=0.3,0.1

Type RM Length L Ch R = 1 ,2882    ,223.1,223.1,223.1
XS GIS Cut Line= 4
2246862.82492185573878.7536987832246834.30681205574159.922394094
 2246853.1936585574363.896483687 2246860.2005215574505.644902473
#Sta/Elev= 30
       0 2375.77     6.5 2371.58    18.5 2366.58    26.6 2357.72    30.6 2356.86
    46.7 2356.53    58.7 2352.03    86.9 2347.25   199.4  2338.5   207.5 2337.08
   219.5 2332.68   259.3 2332.39   303.9 2329.69     312 2332.62     316 2332.96
   395.8 2331.21   428.5 2332.44   432.6 2331.72   436.2 2329.02   444.6 2328.02
   461.72329.029   468.7 2331.13   484.7 2332.04   492.7 2335.25   508.8 2349.35
   520.8 2362.31     532 2372.57   544.8 2382.12   576.8 2403.17   629.4  2432.2
#Mann= 6 ,-1,0
       0     .06       0      60      .1       0     160     .05       0
  352.61      .1       0   436.2    .045       0   461.7      .1       0
#XS Ineff= 2 , 0
          356.82 2350.21
Permanent Ineff=
       F       F
Bank Sta=436.2,461.7
XS Rating Curve= 0 ,0
Exp/Cntr=0.3,0.1

Type RM Length L Ch R = 1 ,2659    ,222,222,222
XS GIS Cut Line= 4
2246739.37763491573878.9446911682246709.64567648574157.830183368
2246628.54940411 574355.900052042246606.87046866574499.703223742
#Sta/Elev= 30
       0  2363.5     6.3 2359.29    10.3 2354.93    14.3 2353.86    26.4 2353.91
    30.4 2352.91    38.5 2346.95    42.5 2345.06    82.7 2335.56   171.2 2331.89
   215.4 2327.97   260.1 2328.52   267.7 2329.43   275.8 2331.85   279.8 2331.83
   288.4 2328.95   305.7 2327.35   353.2  2325.9     379 2327.78   418.1 2326.39
   449.8 2327.66   452.8 2327.54  461.342323.961   469.9 2322.68  486.84 2323.96
   503.9  2336.9   528.1 2362.61   536.2 2369.95   576.5 2397.97   639.9 2438.19
#Mann= 6 ,-1,0
       0     .06       0     160      .1       0     250     .05       0
  310.47      .1       0  461.34    .045       0  486.84      .1       0
#XS Ineff= 2 , 0
          380.52 2355.45
Permanent Ineff=
       F       F
Bank Sta=461.34,486.84
XS Rating Curve= 0 ,0
Exp/Cntr=0.3,0.1

Type RM Length L Ch R = 1 ,2437    ,201.7,201.7,201.7
XS GIS Cut Line= 4
 2246574.2996265573862.819341179 2246526.7541751574084.518308251
2246404.25316884574296.9840950912246398.49180584574497.547876073
#Sta/Elev= 30
       0 2352.86    17.3 2352.68      27 2347.39    43.3 2341.99    51.5 2337.89
    67.8 2336.82    84.2 2333.29   100.6 2331.37   137.4 2329.01   222.7 2326.55
   231.9  2324.6   240.8 2321.05     246 2320.73   255.2 2322.26   264.4 2320.97
   284.8 2321.58   299.4 2319.87   319.8 2321.41   329.1  2320.3   389.1  2321.4
  400.872319.369   407.6 2318.88   422.4 2319.36   430.7 2321.87   442.9 2320.95
   472.3  2324.7   512.2 2353.71   544.2 2374.92   632.3 2425.77   672.6 2452.87
#Mann= 6 ,-1,0
       0     .06       0      70      .1       0     170     .07       0
  276.74      .1       0  400.87    .045       0   422.4      .1       0
#XS Ineff= 2 , 0
                          431.93         2333.11
Permanent Ineff=
       F       F
Bank Sta=400.87,422.4
XS Rating Curve= 0 ,0
Exp/Cntr=0.3,0.1

Type RM Length L Ch R = 1 ,2235    ,241.7,241.7,241.7
XS GIS Cut Line= 4
2246474.41223296573870.0797595372246443.04144532573998.789067044
2246114.14335189574248.0867432762246125.98356084574484.609556235
#Sta/Elev= 30
       0 2352.97     7.3 2350.37    19.7 2343.23    73.9 2328.77   110.2 2324.54
   122.6 2319.29   166.2 2316.81   190.5 2318.46   224.7 2316.77   267.6 2318.53
   295.4 2316.27   315.2 2317.61  329.49 2315.82  344.942315.828     355 2317.48
   361.9 2316.29   370.3 2317.27   407.9 2317.54   433.2 2314.44   484.6 2316.01
   502.5 2315.15   533.7 2316.91   550.3 2315.88   562.3 2318.55   606.3 2346.77
   630.4 2360.35   681.7 2386.51     716 2405.31   750.8 2426.64     782 2448.35
#Mann= 4 ,-1,0
       0     .06       0    73.9      .1       0  329.49    .045       0
  344.94      .1       0
#XS Ineff= 2 , 0
       0                     400       0    2330
Permanent Ineff=
       F       F
Bank Sta=329.49,344.94
XS Rating Curve= 0 ,0
Exp/Cntr=0.3,0.1