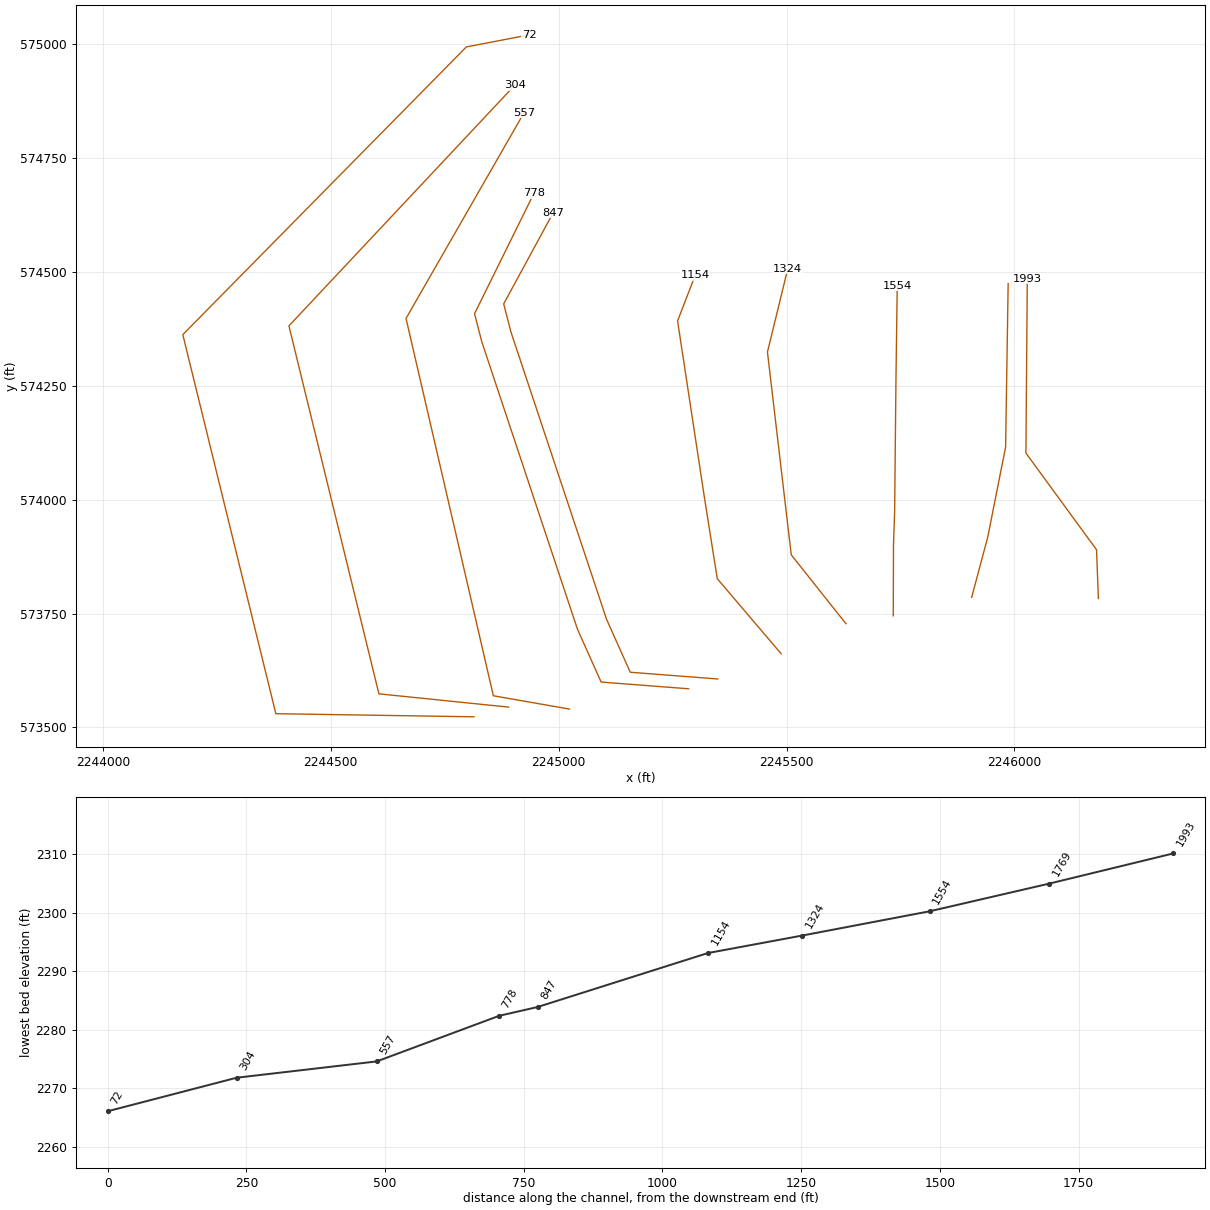
HEC-RAS study CONLEYRN.prj: CONLEYRN

--- CONLEYRN.g01 (geometry) --- (continued)

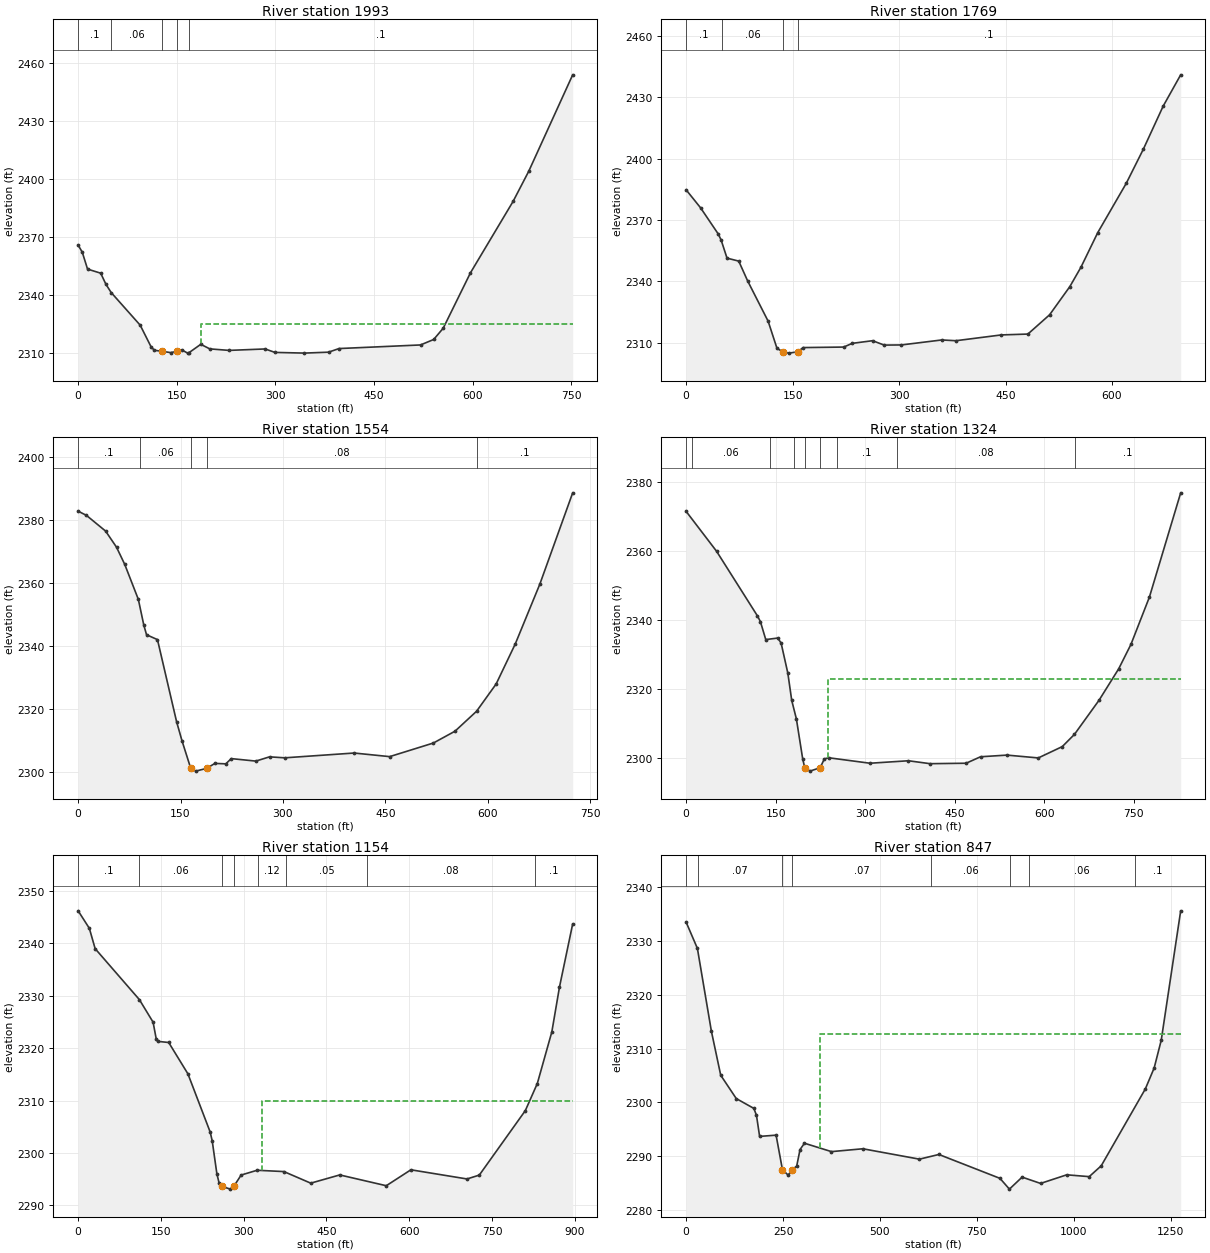
Type RM Length L Ch R = 1 ,1993    ,224.1,224.1,224.1
XS GIS Cut Line= 4
 2246184.1477901573782.8906785332246180.02781764573889.910123852
2246025.12002296574101.9693745942246028.16862249574484.606230401
#Sta/Elev= 30
       0 2365.88     6.3 2362.22    14.3  2353.5    34.3  2351.4    42.3 2345.65
    50.3 2341.39    94.4 2324.56   111.1  2313.3   116.1  2311.6  127.482311.099
   140.9  2310.4   150.8 2311.13     158 2311.75   166.6 2310.14   167.9 2310.19
   186.6 2314.69   200.3 2312.33   229.6 2311.55   284.5 2312.29   299.4 2310.51
   344.2 2310.16   380.9 2310.63   396.9  2312.5   520.9 2314.36   540.9 2317.18
   555.4 2322.99   596.9  2351.6   661.7 2388.42   685.5 2403.97   752.4 2453.76
#Mann= 5 ,-1,0
       0      .1       0    50.3     .06       0  127.48    .045       0
   150.8     .06       0   167.9      .1       0
#XS Ineff= 2 , 0
       0                   186.6       0    2325
Permanent Ineff=
       F       F
Bank Sta=127.48,150.8
XS Rating Curve= 0 ,0
Exp/Cntr=0.3,0.1

Type RM Length L Ch R = 1 ,1769    ,215.5,215.5,215.5
XS GIS Cut Line= 4
2245906.13814821573785.5579505092245941.35513362 573917.43227696
2245980.58096584574115.2595896922245986.17750568574473.792828667
#Sta/Elev= 30
       0  2384.7    20.3 2375.94    45.1 2363.22    49.3 2360.19    57.6 2351.35
    74.1 2349.91    86.6 2340.27   115.5 2320.58     128 2307.29   136.5 2305.57
   144.4 2304.97  156.962305.572   164.8 2307.68   221.9 2307.93   234.1 2309.75
   262.7 2311.04     279 2308.89   303.4 2308.97   360.1  2311.4   380.1 2311.03
   444.1 2313.86   481.5 2314.28   512.1 2323.69   540.6 2337.45   556.3 2346.94
   579.9 2363.79   620.1 2387.89   644.1  2404.5   672.1 2425.57   696.8 2440.87
#Mann= 4 ,-1,0
       0      .1       0      50     .06       0   136.5    .045       0
  156.96      .1       0
Bank Sta=136.5,156.96
XS Rating Curve= 0 ,0
Exp/Cntr=0.3,0.1

Type RM Length L Ch R = 1 ,1554    ,229.2,229.2,229.2
XS GIS Cut Line= 5
2245734.08219142573744.9526899832245734.60855302573901.244935928
2245737.13609632573973.9039004992245739.96832522574259.723545901
2245742.80712196574469.226367802
#Sta/Elev= 30
       0  2382.7    12.2 2381.35    40.2 2376.38    56.2 2371.27    68.2 2365.84
    88.2  2354.7    96.2 2346.53   100.2 2343.49   116.2 2341.95   144.2 2315.92
   152.2 2309.81   164.2 2301.62  165.812301.117   172.2 2300.24   188.2 2301.11
   200.3 2302.69   216.3 2302.55   224.3 2304.21   260.3 2303.42   280.3 2304.77
   302.6 2304.46   404.3 2305.98   456.3 2304.84   520.3 2309.15     552  2312.9
   583.6 2319.23   612.3 2327.89   640.3 2340.58   676.3 2359.56   724.4 2388.51
#Mann= 5 ,-1,0
       0      .1       0      90     .06       0  165.81    .045       0
   188.2     .08       0  584.83      .1       0
Bank Sta=165.81,188.2
XS Rating Curve= 0 ,0
Exp/Cntr=0.3,0.1

Type RM Length L Ch R = 1 ,1324    ,170.5,170.5,170.5
XS GIS Cut Line= 4
2245630.19333094573727.7295312062245510.31867352573878.710013382
 2245458.0719251 574323.650064482245502.61566698 574506.09825618
#Sta/Elev= 30
       0 2371.48    50.9 2359.93   119.2 2341.22   124.4 2339.51   133.4 2334.28
   153.4 2334.72   159.1 2333.28   170.4 2324.52   176.9 2316.62   184.7 2311.26
   195.3 2299.63  198.722297.094   207.4  2296.1  224.562297.089   231.5 2299.64
   238.8 2299.98     308 2298.39   372.5 2299.11   408.7 2298.26   469.1 2298.39
   493.3 2300.27   537.6 2300.75     590 2299.93   630.2 2303.22   650.6 2306.77
   691.8 2316.67   724.7 2325.79   745.3  2332.9   776.2 2346.61   828.6 2376.87
#Mann= 9 ,-1,0
       0      .1       0      10     .06       0     140      .1       0
     180     .06       0  198.72    .045       0  224.56     .06       0
  252.78      .1       0  352.78     .08       0  650.78      .1       0
#XS Ineff= 2 , 0
                          237.42         2322.96
Permanent Ineff=
       F       F
Bank Sta=198.72,224.56
XS Rating Curve= 0 ,0
Exp/Cntr(USF)=0,0
Exp/Cntr=0.3,0.1

Type RM Length L Ch R = 1 ,1154    ,307.1,307.1,307.1
XS GIS Cut Line= 5
2245488.13290892 573661.749922362245348.02601528573826.306538597
2245320.22173084574001.6646866592245260.92731863574391.883164133
2245299.71820973574492.473110267
#Sta/Elev= 30
       0 2346.22    20.3 2342.88    30.8    2339     111 2329.27   135.8 2324.97
   141.4 2321.84   144.3  2321.3   164.1 2321.09   198.9 2315.11   239.3 2303.99
     243 2302.29   251.4 2296.03   255.5 2294.24   260.5 2293.64   275.7  2293.1
   282.3 2293.66   295.4 2295.79   324.3  2296.7   372.9 2296.45   421.5 2294.24
   474.1 2295.81   558.4 2293.75     603 2296.79   704.7 2295.04     727 2295.78
   810.4 2308.09   832.1 2313.26   858.4 2323.11   872.3 2331.69   896.2 2343.72
#Mann= 8 ,-1,0
       0      .1       0     110     .06       0   260.5    .045       0
   282.3     .06       0  326.12     .12       0  376.12     .05       0
  523.67     .08       0  828.37      .1       0
#XS Ineff= 2 , 0
                          333.07         2309.99
Permanent Ineff=
       F       F
Bank Sta=260.5,282.3
XS Rating Curve= 0 ,0
Exp/Cntr(USF)=0,0
Exp/Cntr=0.3,0.1

Type RM Length L Ch R = 1 ,847     ,69.1,69.1,69.1
XS GIS Cut Line= 6
2245349.08207112573606.3456914282245157.10541995573621.114069779
2245105.12697663573737.199259865 2244895.3084317574367.673768618
2244879.40734161574429.2904927082244987.97606443 574629.27091913
#Sta/Elev= 30
       0 2333.48      29 2328.61    65.1 2313.22    89.2 2305.03   129.3  2300.7
   174.7 2298.87   181.4 2297.58   189.5 2293.67     232  2293.9  248.462287.456
   263.4 2286.46   272.1 2287.44   285.1 2288.14   293.8 2291.23   305.2  2292.4
   374.8 2290.84   455.8 2291.37   601.7 2289.44   651.9 2290.31   809.5 2285.87
   833.8 2283.87   866.6  2286.1   914.2 2284.93   981.7 2286.53  1039.6 2286.19
  1070.6  2288.2  1184.4 2302.49  1207.2 2306.39  1225.4 2311.53  1275.6 2335.59
#Mann= 8 ,-1,0
       0      .1       0      30     .07       0  248.46    .045       0
   272.1     .07       0  632.78     .06       0  835.17     .05       0
  885.17     .06       0 1158.01      .1       0
#XS Ineff= 2 , 0
                          345.85         2312.79
Permanent Ineff=
       F       F
Bank Sta=248.46,272.1
XS Rating Curve= 0 ,0
Exp/Cntr(USF)=0,0
Exp/Cntr=0.3,0.1

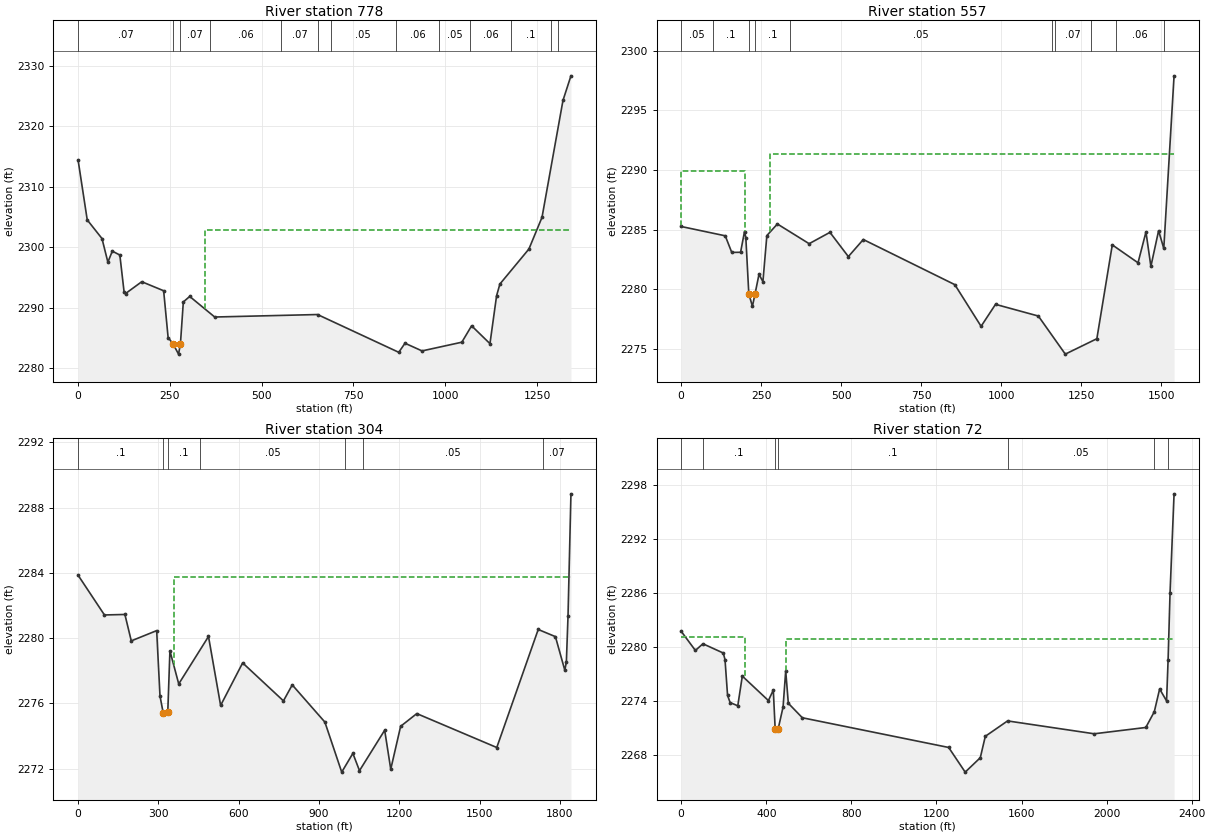
Type RM Length L Ch R = 1 ,778     ,220.7,220.7,220.7
XS GIS Cut Line= 6
2245285.14952727573584.836509951 2245093.1728761573599.604888302
2245041.19443278573715.6900783882244831.37588785574346.164587141
2244815.47479776574407.7813112312244945.78740781574671.848984238
#Sta/Elev= 30
       0 2314.46      25 2304.54    65.2 2301.46    81.2 2297.56    93.3 2299.38
   113.8 2298.74   125.4 2292.63   129.4 2292.38   173.5 2294.33   233.1 2292.84
   245.3 2285.11  258.492284.086   273.7 2282.37  278.88 2284.11   286.7 2290.99
   304.1  2291.9   372.2  2288.5   652.3 2288.91   873.5 2282.67   890.5 2284.17
   936.9  2282.9  1045.3 2284.34  1071.9 2287.05  1121.9  2284.1    1140 2292.03
    1149 2293.95    1228 2299.73  1263.7 2304.97  1320.8 2324.28  1342.5 2328.34
#Mann= 13 ,-1,0
       0     .07       0  258.49    .045       0  278.88     .07       0
  359.82     .06       0  552.78     .07       0  652.78     .06       0
  688.15     .05       0  865.17     .06       0  984.38     .05       0
 1068.01     .06       0 1178.01      .1       0 1288.01     .06       0
 1308.01      .1       0
#XS Ineff= 2 , 0
                          345.05         2302.91
Permanent Ineff=
       F       F
Bank Sta=258.49,278.88
XS Rating Curve= 0 ,0
Exp/Cntr(USF)=0,0
Exp/Cntr=0.3,0.1

Type RM Length L Ch R = 1 ,557     ,252.6,252.6,252.6
XS GIS Cut Line= 4
2245023.78621354573540.280837141 2244856.7568201573569.545714854
 2244665.1478041574397.406358883 2244924.2366655574848.982813592
#Sta/Elev= 30
       0 2285.26   137.7 2284.48     158 2283.09   185.6  2283.1   197.9 2284.84
     202 2284.33  211.292279.634   222.6 2278.57   230.8 2279.62   243.1 2281.25
   255.4 2280.64   267.7  2284.5   300.6 2285.47   399.8 2283.82   464.8 2284.77
   522.3 2282.74     569 2284.17   854.9 2280.39     937  2276.9   982.1 2278.74
  1115.9 2277.76  1200.1 2274.57  1298.7 2275.86  1346.9 2283.72  1427.3 2282.22
  1452.1  2284.8  1467.5 2281.92  1491.6 2284.91  1507.8 2283.42  1539.9 2297.88
#Mann= 10 ,-1,0
       0     .05       0     100      .1       0  211.29    .045       0
   230.8      .1       0  339.57     .05       0 1159.32     .06       0
 1169.32     .07       0 1279.32     .05       0 1359.32     .06       0
 1509.32     .07       0
#XS Ineff= 2 , 0
          198.36 2289.88  277.67         2291.37
Permanent Ineff=
       F       F
Bank Sta=211.29,230.8
XS Rating Curve= 0 ,0
Exp/Cntr(USF)=0,0
Exp/Cntr=0.3,0.1

Type RM Length L Ch R = 1 ,304     ,232.3,232.3,232.3
XS GIS Cut Line= 4
  2244890.274231573544.6108039812244605.66424554 573573.75945509
2244408.22264029574381.0146557082244903.82877385574909.092652009
#Sta/Elev= 30
       0 2283.86    98.6 2281.42     175 2281.45   198.8 2279.83   293.7 2280.46
   306.1 2276.45   317.82275.436  335.162275.461   343.2 2279.22   376.1 2277.19
   487.3  2280.1   532.6 2275.87   614.9 2278.48   767.3 2276.15   800.2 2277.13
   922.1 2274.85     985 2271.78  1026.7 2272.93  1051.4 2271.87  1145.5 2274.35
  1168.2 2271.96  1205.1 2274.59  1265.5 2275.37  1564.3 2273.29  1719.1 2280.53
  1783.4 2280.09  1818.5 2278.03  1824.3 2278.54  1830.4 2281.33  1841.4 2288.85
#Mann= 7 ,-1,0
       0      .1       0   317.8    .045       0  335.16      .1       0
   456.1     .05       0   996.1      .1       0  1066.1     .05       0
 1737.15     .07       0
#XS Ineff= 2 , 0
                          358.39         2283.74
Permanent Ineff=
       F       F
Bank Sta=317.8,335.16
XS Rating Curve= 0 ,0
Exp/Cntr(USF)=0,0
Exp/Cntr=0.3,0.1

Type RM Length L Ch R = 1 ,72      ,,,
XS GIS Cut Line= 5
2244814.24135834573523.3851739182244379.52680797573530.198305052
2244175.43465475574361.8388482152244797.40805623 574992.93556084
2244934.74035295575019.362782882
#Sta/Elev= 30
       0  2281.7    66.8 2279.57   102.3 2280.31   198.1 2279.28   206.1 2278.54
   218.1 2274.57   230.1 2273.78   266.1 2273.42   287.4 2276.72   410.1    2274
   433.1 2275.17     442 2270.79  455.332270.789     479 2273.28   491.4  2277.3
   503.7  2273.7   569.6 2272.09  1257.5 2268.79  1335.1 2266.05  1406.1 2267.65
  1429.7 2270.03  1534.4 2271.74  1941.6 2270.31  2184.1 2271.01  2224.1 2272.76
  2249.2 2275.29  2281.8 2273.96    2289 2278.54  2298.1 2285.96    2317 2296.97
#Mann= 7 ,-1,0
       0     .05       0   102.3      .1       0     442    .045       0
  455.33      .1       0  1534.4     .05       0  2224.1     .06       0
    2289     .07       0
#XS Ineff= 2 , 0
       0   299.6 2281.05   491.4       0 2280.83
Permanent Ineff=
       F       F
Bank Sta=442,455.33
XS Rating Curve= 0 ,0
Exp/Cntr(USF)=0,0
Exp/Cntr=0.3,0.1
LCMann Table=0

Chan Stop Cuts=-1
Use User Specified Reach Order=0
Composite Channel Slope=5